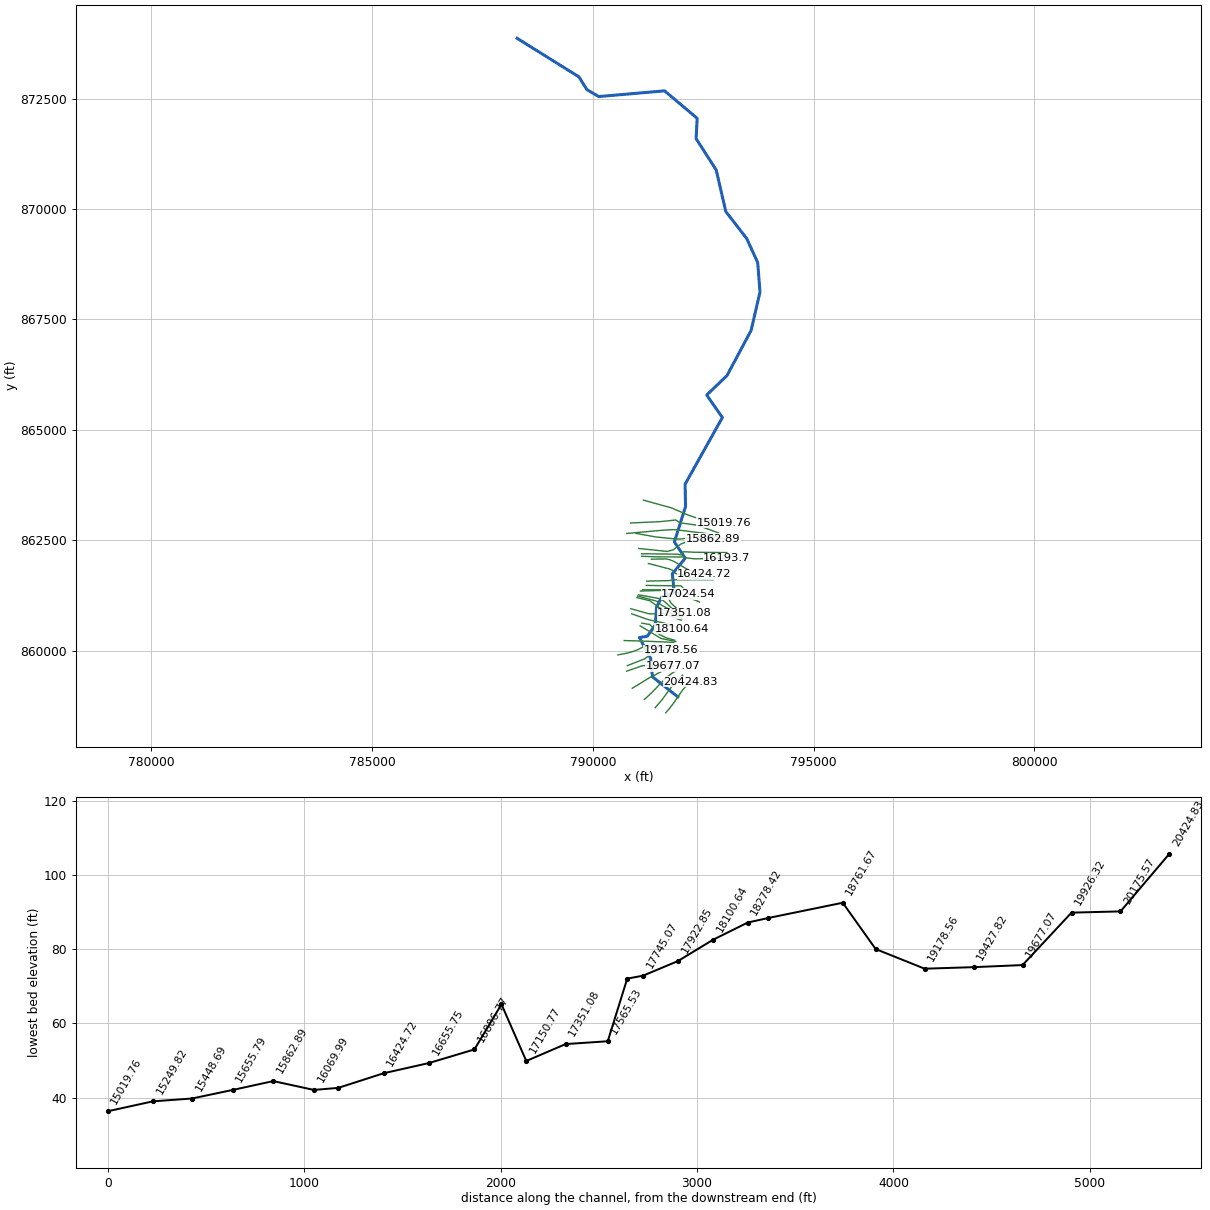
--- 16165_ras.prj (project) ---

Proj Title=16165
Current Plan=p01
Default Exp/Contr=0.3,0.1
English Units
Geom File=g01
Flow File=f01
Plan File=p01
Y Axis Title=Elevation
X Axis Title(PF)=Main Channel Distance
X Axis Title(XS)=Station
BEGIN DESCRIPTION:
RFD model 16165 exported to HEC-RAS
END DESCRIPTION:

--- 16165_ras.p01 (plan) ---

Plan Title=Plan 01
Program Version=4.10
Short Identifier=Plan 01
Geom File=g01
Flow File=f01
Subcritical Flow
Calc Critical at every XS
Secant Critical Depth

--- 16165_ras.f01 (steady flow) ---

Flow Title=Flow 01
Program Version=5.01
Number of Profiles= 6
Profile Names=10yr,25yr,50yr,100yr,100plus,500yr
River Rch & RM=16165,56,20424.83
  553.36  877.64 1179.22  1449.5 2116.27 3073.02
River Rch & RM=16165,56,20175.57
  600.62  952.15 1279.02 1571.62 2294.56 3291.15
River Rch & RM=16165,56,19926.32
  614.31  973.89  1308.3 1607.61 2347.12 3355.79
River Rch & RM=16165,56,19677.07
  664.91 1054.96 1418.04 1743.21 2545.08 3600.51
River Rch & RM=16165,56,19427.82
  668.83  1061.2 1426.45 1753.54 2560.17 3618.83
River Rch & RM=16165,56,19178.56
  673.38 1068.43 1436.21 1765.55 2577.71 3640.15
River Rch & RM=16165,56,18929.31
  711.92 1130.42 1520.33  1869.7 2729.77 3826.93
River Rch & RM=16165,56,18761.67
  728.49 1157.09 1556.57  1914.6 2795.32 3907.15
River Rch & RM=16165,56,18381.27
  732.23 1163.09 1564.68 1924.63 2809.96 3924.89
River Rch & RM=16165,56,18278.42
  753.89 1197.69 1611.46 1982.32 2894.19 4026.29
River Rch & RM=16165,56,18100.64
  755.12 1199.68 1614.14 1985.64 2899.04 4032.14
River Rch & RM=16165,56,17922.85
  760.69 1208.59 1626.22 2000.56 2920.82 4058.41
River Rch & RM=16165,56,17745.07
  766.86 1218.49 1639.62 2017.12 2944.99 4087.52
River Rch & RM=16165,56,17565.53
  768.09 1220.46  1642.3 2020.43 2949.82 4093.34
River Rch & RM=16165,56,17351.08
  774.43 1230.68 1656.18 2037.63 2974.94  4123.8
River Rch & RM=16165,56,17150.77
  788.58 1253.35 1686.88 2075.56 3030.31 4190.23
River Rch & RM=16165,56,17024.54
  789.75 1255.25 1689.47 2078.78 3035.02 4195.98
River Rch & RM=16165,56,16886.77
  790.93 1257.16 1692.08 2082.02 3039.75 4201.74
River Rch & RM=16165,56,16655.75
  793.27 1260.95 1697.26 2088.47 3049.17 4213.23
River Rch & RM=16165,56,16424.72
  795.31 1264.27 1701.78 2094.11  3057.4 4223.28
River Rch & RM=16165,56, 16193.7
 1214.84 1928.35 2594.17 3188.38 4655.03 6040.14
River Rch & RM=16165,56,16069.99
  1216.7 1931.38 2598.32 3193.56  4662.6 6048.87
River Rch & RM=16165,56,15862.89
 1218.03 1933.55 2601.29 3197.26    4668  6055.1
River Rch & RM=16165,56,15655.79
 1220.95 1938.31 2607.81 3205.39 4679.87 6068.79
River Rch & RM=16165,56,15448.69
 1323.54 2106.11 2838.13 3493.18 5100.05 6552.95
River Rch & RM=16165,56,15249.82
 1327.64 2112.84 2847.36 3504.72  5116.9 6572.26
River Rch & RM=16165,56,15019.76
 1332.15 2120.26  2857.6 3517.58 5135.66 6593.96
River Rch & RM=16165,56, 14789.7
 1336.85 2128.03 2868.34 3531.08 5155.37 6616.83
River Rch & RM=16165,56,14559.63
 1339.08 2131.72 2873.43 3537.48 5164.71 6627.66
River Rch & RM=16165,56,14329.57
 1343.29 2138.68 2883.05 3549.55 5182.35 6648.08
River Rch & RM=16165,56,14099.51
 1347.49 2145.62 2892.64 3561.61 5199.95 6668.49
River Rch & RM=16165,56,13869.45
 1354.36    2157 2908.38 3581.41 5228.86 6702.04
River Rch & RM=16165,56,13639.39
 1625.09 2609.93 3538.96 4379.22 6393.66 8051.24
River Rch & RM=16165,56,13409.33
 1750.52    2817 3824.98 4738.56 6918.29 8636.67
River Rch & RM=16165,56, 12949.2
 1755.76 2825.83 3837.31 4754.21 6941.14 8662.66
River Rch & RM=16165,56, 12649.2
 1760.13 2833.17 3847.58 4767.24 6960.17 8684.29
River Rch & RM=16165,56,12393.46
 1764.71 2840.89 3858.35 4780.92 6980.14 8706.99
River Rch & RM=16165,56,12005.57
 1793.88 2890.17 3927.42 4868.79 7108.44  8853.4
River Rch & RM=16165,56, 11884.9
 1794.52 2891.25 3928.93 4870.72 7111.25 8856.62
River Rch & RM=16165,56,11427.15
 1824.18 2941.92 4000.39 4962.15 7244.75 9010.59
River Rch & RM=16165,56,10969.41
 1874.01  3027.2 4120.85 5116.46 7470.03 9270.22
River Rch & RM=16165,56,10282.79
 1881.66 3040.33  4139.4 5140.25 7504.76 9310.23
River Rch & RM=16165,56,9596.174
  2131.7 3464.69  4735.9 5901.22 8615.7810561.56
River Rch & RM=16165,56,9464.987
 2132.98 3466.93 4739.11 5905.37 8621.8510568.57
River Rch & RM=16165,56,8770.299
 2203.79 3590.36 4915.42 6133.46 8954.8510951.23
River Rch & RM=16165,56, 8075.61
 2220.63 3620.01 4958.01 6188.83 9035.6911044.85
River Rch & RM=16165,56, 7799.61
 2222.94 3624.06 4963.84  6196.4 9046.7411057.63
River Rch & RM=16165,56, 7337.43
 2272.47 3711.56 5089.83 6360.49 9286.3111335.53
River Rch & RM=16165,56,6569.819
 2284.45 3732.73 5120.31 6400.19 9344.2811402.65
River Rch & RM=16165,56,6305.819
 2288.04 3739.09  5129.5  6412.2 9361.8111423.04
River Rch & RM=16165,56,5518.234
 2443.26 4007.54 5511.38 6904.5110080.5812230.42
River Rch & RM=16165,56,4775.894
 2469.19 4053.21 5577.07 6989.9910205.3812372.81
Boundary for River Rch & Prof#=16165,56,1
Up Type= 0
Dn Type= 2
Boundary for River Rch & Prof#=16165,56,2
Up Type= 0
Dn Type= 2
Boundary for River Rch & Prof#=16165,56,2
Up Type= 0
Dn Type= 2
Boundary for River Rch & Prof#=16165,56,2
Up Type= 0
Dn Type= 2
Boundary for River Rch & Prof#=16165,56,2
Up Type= 0
Dn Type= 2
Boundary for River Rch & Prof#=16165,56,2
Up Type= 0
Dn Type= 2

--- 16165_ras.g01 (geometry) ---

Geom Title=16165
Program Version=4.10

River Reach=16165,56
Reach XY= 30
791925.883629249858949.172908551791351.165207382859404.987894779
791310.211427689859820.992078026791055.617109418860292.892811328
791234.989178181860323.912041262791417.266044823860579.714733545
791444.031814694860983.407842919791570.082502188861225.974441031
791844.818919451861320.012109553791801.494314193861737.442436278
792094.761258185862091.727380052 791848.11831254862458.172392904
792100.954900741863263.209331917792090.205796094863767.600089245
792935.140856858865278.460707243792580.457775268865788.891294485
793040.259174553866229.268127611793586.734328328867253.662533219
793787.390956432868121.912651767  793735.3098509868790.808413564
793486.669951589869334.114422025793013.478373705869944.794664799
792795.403153564870887.937445744792339.673212408871597.783513056
792364.553348603872058.244509553791625.715926109872680.055754503
790132.229204125 872550.92219951789863.539198221872710.098743243
789683.988056865872997.889934422788284.610306205873870.641095713

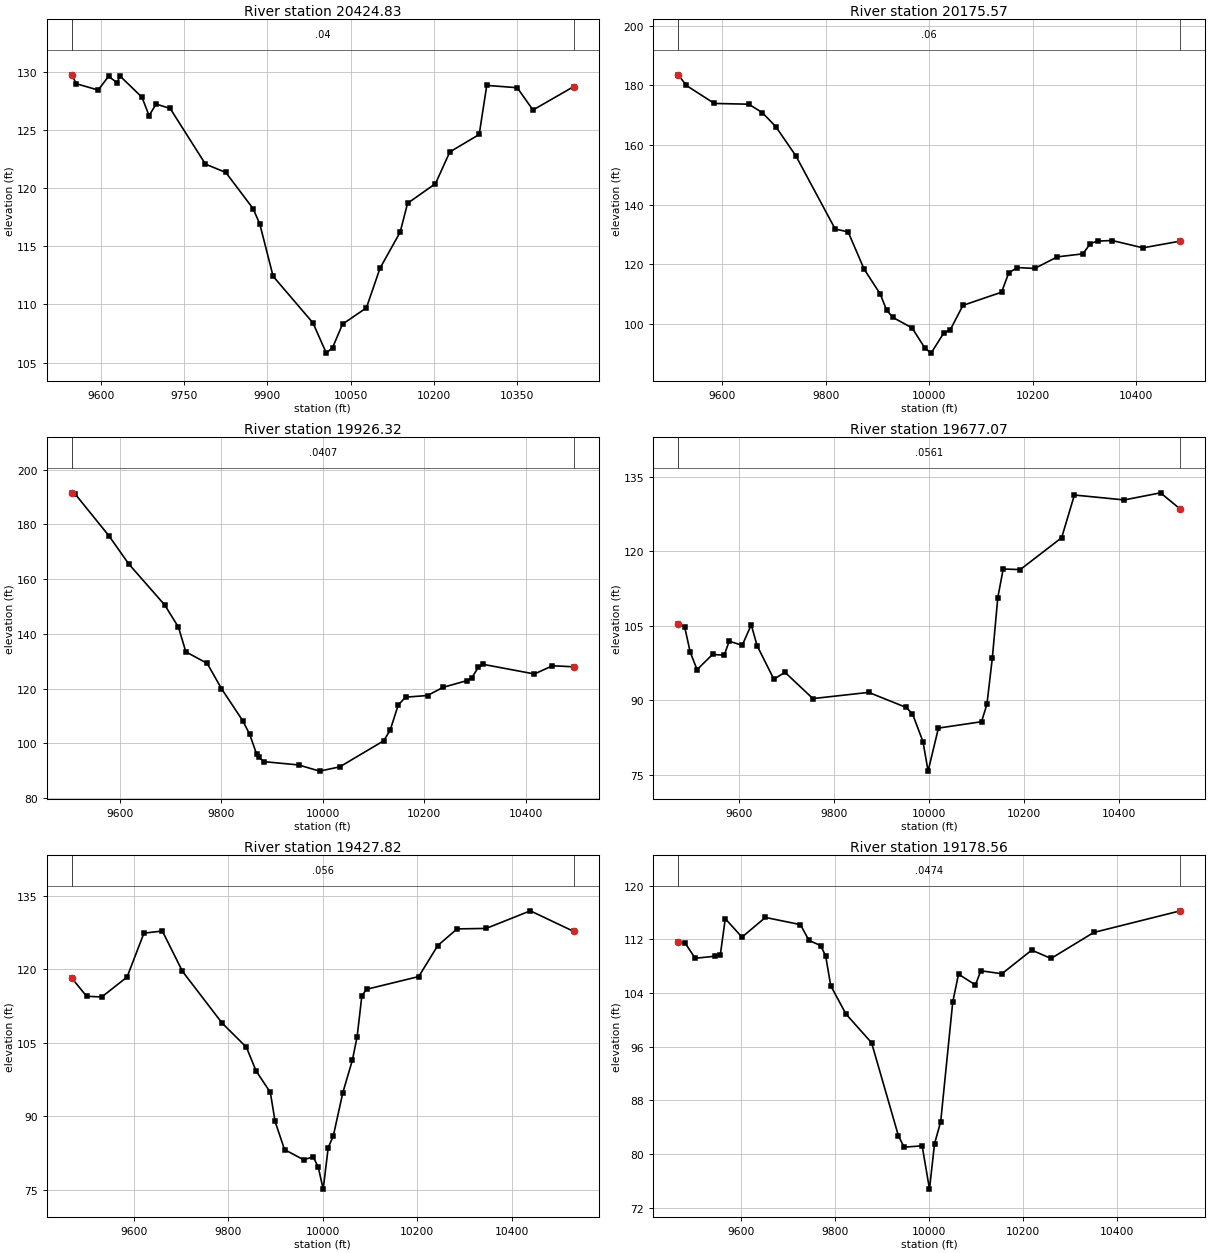
Type RM Length L Ch R = 1 ,20424.83,249.252800,249.252800,249.252800
XS GIS Cut Line= 6
791651.760988888858588.842055198791735.881820054 858686.70822463
791809.452682053858780.908030672792033.289282477859102.467254972
792127.610991893859210.778828504792216.100731815859295.286714317
#Sta/Elev= 30
9546.739129.73669554.859128.97189594.418128.42839613.072129.59959628.413129.0726
9633.978129.62929673.537 127.807 9686.31126.22369698.999127.22519724.376126.8455
9788.081122.06259824.911121.3421 9874.05118.24169886.265116.9081 9910.26112.4224
9982.245108.409610006.34105.813810017.69  106.2910035.58108.305610078.69109.7028
10103.27113.112810139.63116.211410153.03118.693510203.43120.384310229.34123.1096
10282.35124.608510296.04  128.8310351.05128.628310379.43126.712510453.25128.7307
#Mann= 3 , 0 , 0
9546.739    0.04       09546.739    0.04       010453.25    0.04       0
#XS Ineff= 2 , 0
       0                               0
Bank Sta=9546.739,10453.25
Exp/Cntr=0.3,0.1

Type RM Length L Ch R = 1 ,20175.57,249.252800,249.252800,249.252800
XS GIS Cut Line= 6
791411.981545803858703.389709573791573.527247683858890.140835673
791776.152811738859168.331190021791850.877745179859262.461967622
791945.419915205859362.308495944792037.023175703859441.623437015
#Sta/Elev= 30
9514.933183.50789530.629179.93549584.708173.91489651.298173.66249677.284170.8457
9703.271 166.1819742.251156.34189818.167131.83429843.242130.85679874.024118.4074
9905.261110.04379917.535104.6483 9929.81102.18789966.89598.663799991.18292.01464
10003.4690.23429 10028.196.9898610040.4297.9986110065.05106.240610139.73110.6566
10153.49117.106610169.91118.914610203.68118.610810247.39   122.510297.11123.5121
10311.07126.945310325.22127.785310353.52127.973510412.83125.519310485.07127.7766
#Mann= 3 , 0 , 0
9514.933    0.06       09514.933    0.06       010485.07    0.06       0
#XS Ineff= 2 , 0
       0                               0
Bank Sta=9514.933,10485.07
Exp/Cntr=0.3,0.1

Type RM Length L Ch R = 1 ,19926.32,249.252800,249.252800,249.252800
XS GIS Cut Line= 6
791170.670454938858892.012707912791334.523553184859044.469548922
791582.823418499859302.927533676791667.746442898859384.778275614
791764.518024929 859463.92539013791900.486588279859554.592533301
#Sta/Elev= 30
9505.619191.51569511.449191.26289578.788175.82379617.822 165.5479688.534150.5895
 9715.78142.4423  9730.2 133.4619772.306129.24449800.377120.02899842.145108.3573
9855.913 103.3689869.68196.091759873.64795.085259883.44893.371139952.28792.15707
9993.59189.9006210033.3791.4635710119.68100.952810132.56104.8227 10148.5114.0323
10162.91116.898810206.16117.514310236.98120.499710283.75122.941510293.47124.0322
10306.14127.753110316.33128.866910416.74125.374510452.29128.372310494.34127.9917
#Mann= 3 , 0 , 0
9505.619  0.0407       09505.619  0.0407       010494.34  0.0407       0
#XS Ineff= 2 , 0
       0                               0
Bank Sta=9505.619,10494.34
Exp/Cntr=0.3,0.1

Type RM Length L Ch R = 1 ,19677.07,249.252800,249.252800,249.252800
XS GIS Cut Line= 6
790893.531752454859144.153725332791303.053845587859394.920824228
 791378.88414068859429.399101048791497.621974274859495.276601755
791567.665363359859530.858386268791823.197208837859645.907845945
#Sta/Elev= 30
9470.902105.27859484.381104.78099496.13499.681149510.58196.157659543.14499.20761
9567.68299.069119578.402101.8781 9605.75101.04859624.784105.17649637.166100.9775
9672.424 94.2364 9695.9395.618629754.693 90.33489872.32691.583679951.11988.56458
9964.49787.289659986.71181.686899997.50475.7462310019.2984.4031310110.0885.68225
10121.5189.1892110132.9598.5482510144.39 110.63710155.82116.403810191.72 116.279
10278.99122.694110305.85131.278510410.93130.290710487.37131.720410529.08 128.437
#Mann= 3 , 0 , 0
9470.902  0.0561       09470.902  0.0561       010529.08  0.0561       0
#XS Ineff= 2 , 0
       09880.521                       0
Bank Sta=9470.902,10529.08
Exp/Cntr=0.3,0.1

Type RM Length L Ch R = 1 ,19427.82,249.252800,249.252800,249.252800
XS GIS Cut Line= 6
790765.814584123859532.155832887 791127.59192984859655.759507901
791211.135257754859661.756380149791327.208532328859633.901883931
791442.361778527859633.788098283791793.280711333 859717.56293173
#Sta/Elev= 30
9468.407118.20819499.709114.49519531.884114.3458 9585.51118.41059621.246127.3576
9660.228 127.7869702.738119.58189786.854109.01639838.246104.10019858.65199.28925
9888.89694.886749898.96188.974019918.96183.237799959.20981.184089979.74981.74299
9990.273 79.687210000.8475.1840410011.4883.66341 10022.1 85.962710042.4694.86461
 10062.7101.492110072.72106.269610082.73114.620110092.75115.913910203.14118.5083
10243.51124.834210284.37128.223310345.94128.315710439.44131.905110531.61127.6938
#Mann= 3 , 0 , 0
9468.407   0.056       09468.407   0.056       010531.61   0.056       0
#XS Ineff= 2 , 0
       0                               0
Bank Sta=9468.407,10531.61
Exp/Cntr=0.3,0.1

Type RM Length L Ch R = 1 ,19178.56,249.252800,249.252800,249.252800
XS GIS Cut Line= 6
790781.110970837 859657.48724602 791170.92682278859809.053974248
791335.830063973859928.567857804791425.128529008859971.587419117
791565.597654649860000.227769599791769.264544153860008.751823807
#Sta/Elev= 30
9465.258111.54889480.083111.42339501.432109.1824 9544.13109.48739554.805109.6544
9565.479115.07879601.074112.32979650.875115.26739725.597114.1946 9743.61111.8436
9768.552111.07579779.314109.50929790.075105.08699822.386 100.8839877.114 96.5817
9934.40382.676099946.37881.026899984.80181.2223310000.4374.7703110011.1481.52013
10024.2884.8265810049.96 102.65810062.25106.813110098.32105.203510109.74107.3189
10154.62106.871510218.12110.391810259.38109.155410350.23 113.02510534.67116.2523
#Mann= 3 , 0 , 0
9465.258  0.0474       09465.258  0.0474       010534.67  0.0474       0
#XS Ineff= 2 , 0
       0                               0
Bank Sta=9465.258,10534.67
Exp/Cntr=0.3,0.1

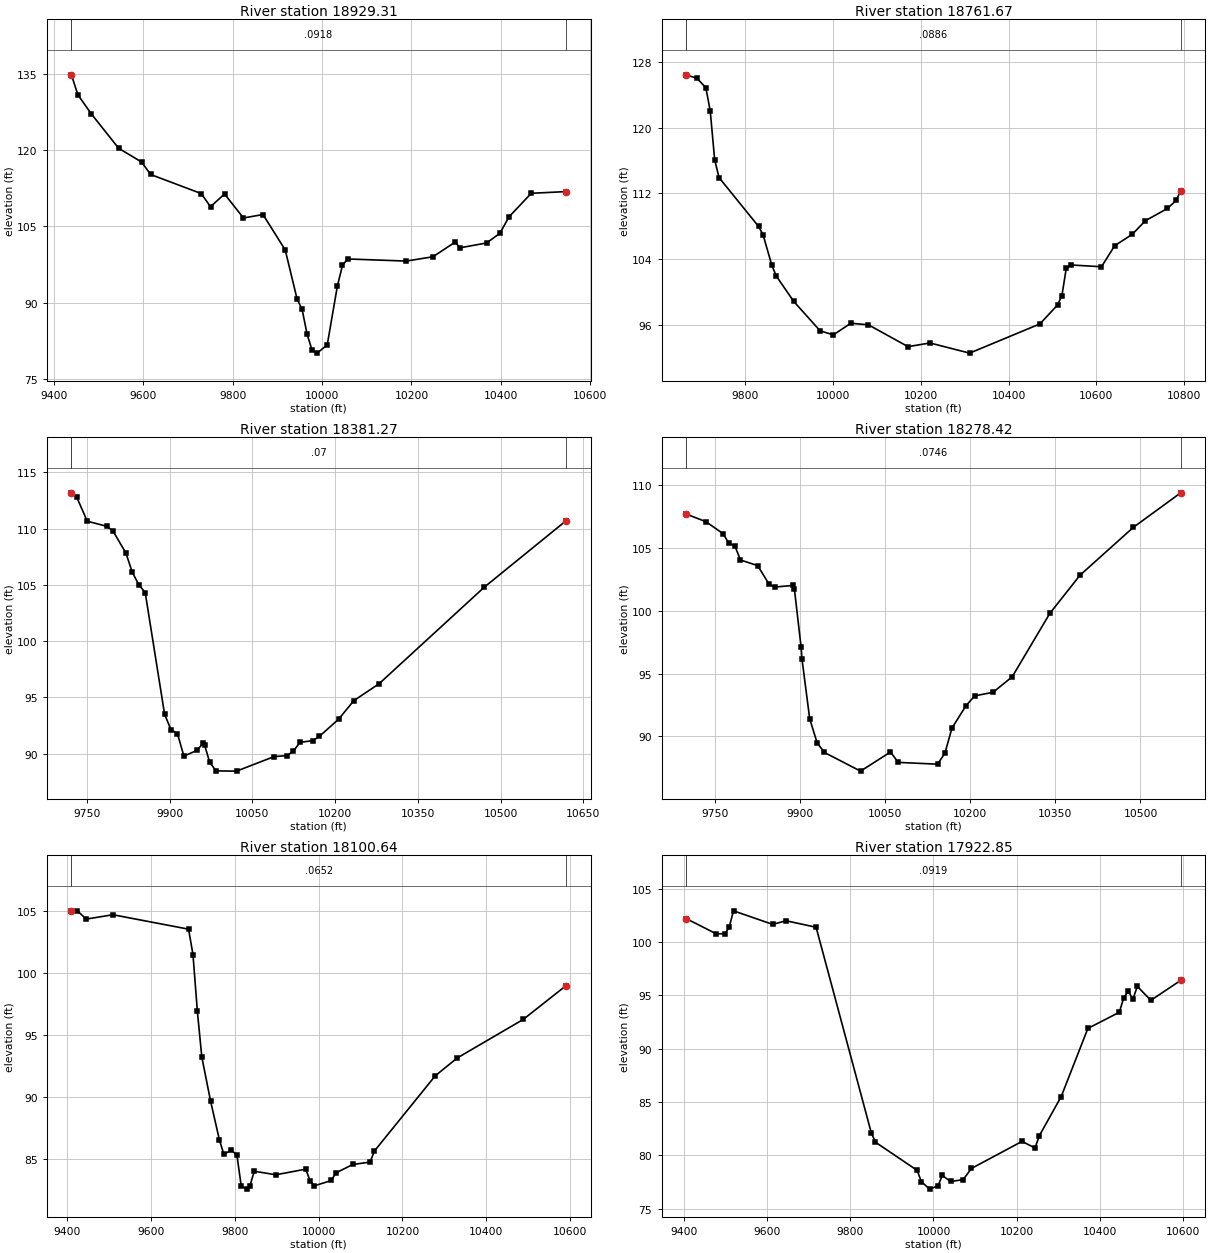
Type RM Length L Ch R = 1 ,18929.31,167.637900,167.637900,167.637900
XS GIS Cut Line= 6
790570.670938164859901.293427885790778.489744127859940.951293796
790914.673922241859978.397147551791026.209314018860022.365841687
791163.173458755 860093.90536496791642.285153836860078.455526143
#Sta/Elev= 30
9438.917134.7621 9453.46  130.839483.908127.04349544.805120.3188 9595.87117.6363
9616.303 115.1749729.453111.42959750.339108.84389781.684111.34379824.021106.6299
9867.798107.3024 9917.53 100.3489944.06290.70332 9955.2988.667239966.51883.77569
9977.74680.602829988.97480.0678210011.5781.6888110034.2893.2614310045.6397.29686
10056.9998.5768410188.1698.1605510248.1999.0032810298.21 101.90610308.22100.7577
10368.25101.717810398.27103.630110418.28106.8454 10468.3111.480410545.63111.8131
#Mann= 3 , 0 , 0
9438.917  0.0918       09438.917  0.0918       010545.63  0.0918       0
#XS Ineff= 2 , 0
       0                10079.49       0
Bank Sta=9438.917,10545.63
Exp/Cntr=0.3,0.1

Type RM Length L Ch R = 1 ,18761.67,380.405000,380.405000,380.405000
XS GIS Cut Line= 3
 790710.35959363860225.459702775791106.866271883860214.670405418
791835.143844306860184.999837637
#Sta/Elev= 30
9666.389126.42549691.039125.99629711.046124.8545 9721.05122.01779731.054116.1199
9741.057113.92519831.091107.98059841.094106.99999861.102103.28479871.106101.9668
 9911.1298.857879971.14395.2833710001.1594.7883610041.1796.2066310081.1996.01154
10171.2793.3570910221.3193.8039910311.3892.5693410471.5296.1246710511.5598.42495
10521.56   99.5710531.56102.929310541.57103.295310611.63103.077910641.66105.6343
10681.69107.024510711.71108.682410761.76110.165610781.77111.156410791.92112.3462
#Mann= 3 , 0 , 0
9666.389  0.0886       09666.389  0.0886       010791.92  0.0886       0
#XS Ineff= 2 , 0
       0                10083.21       0
Bank Sta=9666.389,10791.92
Exp/Cntr=0.3,0.1

Type RM Length L Ch R = 1 ,18381.27,102.844900,102.844900,102.844900
XS GIS Cut Line= 3
791070.452393264860559.927921206791547.878801852860271.314216584
791879.649695963860203.881108031
#Sta/Elev= 30
9721.978113.18969731.503 112.8279750.662110.66719785.718110.21839797.403109.7966
9820.773107.83479832.459  106.129844.144105.02189855.829104.31319890.88593.50945
 9902.5792.113559914.25591.77256 9925.94 89.77069949.31190.270449960.996 90.9153
 9963.4690.761059972.68189.221419984.36688.4560310021.4588.4354510089.5389.72992
 10112.989.8142110124.5990.2215110136.2790.9899210159.6491.1512910171.3391.51561
10206.3993.0505610234.0894.7052910279.8696.2092410470.81 104.80810618.42110.6897
#Mann= 3 , 0 , 0
9721.978    0.07       09721.978    0.07       010618.42    0.07       0
#XS Ineff= 2 , 0
       0                               0
Bank Sta=9721.978,10618.42
Exp/Cntr=0.3,0.1

Type RM Length L Ch R = 1 ,18278.42,177.785200,177.785200,177.785200
XS GIS Cut Line= 6
791110.731211871860619.319829538791293.813392043860588.724127382
791431.991679907860426.615719438791517.410817951860358.048486829
791673.685375482860282.838600606 791856.12539655860233.330559954
#Sta/Elev= 30
9699.514107.69659734.258107.09119764.674106.12929774.813105.35719784.952105.1875
 9795.09104.04399825.506103.59269845.784102.09099855.922101.88819886.927102.0143
9890.107101.74159902.02297.075959903.45696.174479917.11791.395539930.15589.49366
9942.92988.7191210006.7387.2330310059.4688.7558610073.1487.9293310142.38 87.7858
10155.4688.6700810167.8390.6606410192.5892.4435610207.9493.2275110240.1293.50591
10274.0194.7445310340.3599.7945310393.61102.836810487.46106.6398 10570.9109.3889
#Mann= 3 , 0 , 0
9699.514  0.0746       09699.514  0.0746       0 10570.9  0.0746       0
#XS Ineff= 2 , 0
       0                               0
Bank Sta=9699.514,10570.9
Exp/Cntr=0.3,0.1

Type RM Length L Ch R = 1 ,18100.64,177.785300,177.785300,177.785300
XS GIS Cut Line= 6
 790881.62929536 860830.51718966791231.015513028860707.927475644
791319.541653403860684.113487825791537.345399926860638.482832653
791640.964267211 860612.71905443792011.578305754 860494.65189774
#Sta/Elev= 30
9409.877105.02149424.085105.04329445.337104.37619509.093104.72719689.555103.5608
9700.089101.50969710.62496.907619721.15993.232149742.22889.647769763.29886.51434
9773.83385.364769791.43985.706559805.00785.305189815.36382.780559829.93582.55289
9836.07482.827379846.42983.998819897.84183.712239969.32684.166729979.53883.22259
 9989.75 82.822610030.6483.2501410040.8683.8578910081.7684.5463910122.8784.73912
10133.1885.6320910278.4991.7127210330.7793.1494410488.5596.2698710590.1498.98444
#Mann= 3 , 0 , 0
9409.877  0.0652       09409.877  0.0652       010590.14  0.0652       0
#XS Ineff= 2 , 0
       09912.512                       0
Bank Sta=9409.877,10590.14
Exp/Cntr=0.3,0.1

Type RM Length L Ch R = 1 ,17922.85,177.785200,177.785200,177.785200
XS GIS Cut Line= 6
790856.675025765860948.543058405791252.421066547 860836.71399942
 791354.80124327860828.650031949791521.645321828860839.348650597
791638.293431135860823.215622795792001.230620444860687.056699411
#Sta/Elev= 30
9406.189102.21319477.796 100.7939498.757100.78669509.237101.39159519.717102.9416
9614.041101.66579645.482102.01359718.121101.39979850.578 82.12539860.64581.23424
9960.797 78.59039970.84277.533679990.94476.8298810011.0477.1403110021.09 78.1137
10041.1877.54603 10071.277.7179810091.2278.7700310212.7481.3090210243.8980.68988
10254.2881.8421210306.8185.5137510370.8291.9062810446.3493.4232310457.1794.79737
10467.9995.4231910478.8194.6313710489.6495.8501710522.1194.5448210593.7996.41503
#Mann= 3 , 0 , 0
9406.189  0.0919       09406.189  0.0919       010593.79  0.0919       0
#XS Ineff= 2 , 0
       0                               0
Bank Sta=9406.189,10593.79
Exp/Cntr=0.3,0.1

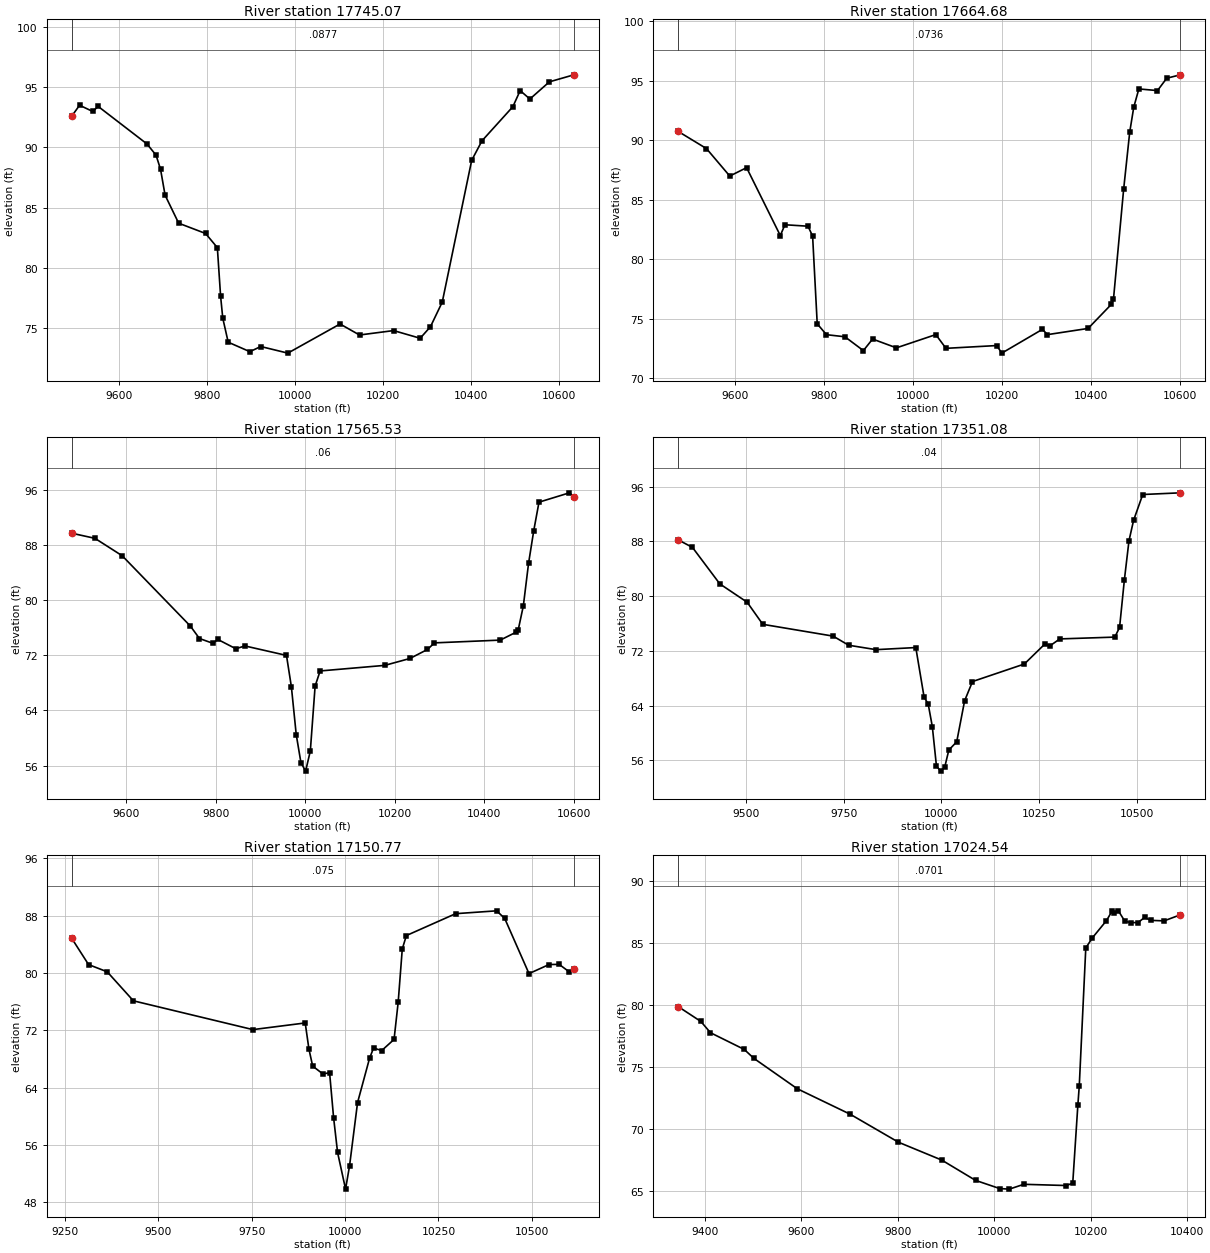
Type RM Length L Ch R = 1 ,17745.07,80.383400,80.383400,80.383400
XS GIS Cut Line= 4
790998.973298202861199.193790299791287.587002854 861129.06335741
791508.767598878860969.921221209792025.305210392860725.813368243
#Sta/Elev= 30
 9492.2892.608729510.04293.513339539.64692.999879552.39393.412419663.13890.29181
 9683.7289.361039694.01188.180949704.30286.028549735.17583.69584 9796.2582.84156
9823.06481.662489830.494 77.60189835.38375.792999847.70373.791959896.98173.00242
 9921.6273.432759983.21772.8819910101.85 75.306810146.0974.3913510223.5274.75871
10283.93 74.118910307.33 75.082210334.1277.1334710400.9588.9282810424.3690.55276
10494.5793.3947910511.0994.7328710533.2194.0310410577.4595.4605110633.0996.04482
#Mann= 3 , 0 , 0
 9492.28  0.0877       0 9492.28  0.0877       010633.09  0.0877       0
#XS Ineff= 2 , 0
       09912.827        10072.07       0
Bank Sta=9492.28,10633.09
Exp/Cntr=0.3,0.1

Type RM Length L Ch R = 1 ,17664.68,99.158200,99.158200,99.158200
XS GIS Cut Line= 4
791013.808582127861235.607668936791461.564422905 861112.87941134
791542.484153181861036.005667597792026.653872609860770.319219902
#Sta/Elev= 30
9473.17190.734759536.61989.292099588.95786.982449626.78687.68874 9702.5281.97664
9712.88982.886149764.73382.763419775.10281.934539785.47174.553619806.20973.63896
9847.68473.46312 9889.1672.300449909.89773.272329963.40172.5317610051.9273.64701
10074.7472.49101 10188.872.7244710200.2172.0875310291.4674.0880510302.8773.64362
10394.1374.1642410446.0976.1792910451.1676.6316110473.97 85.861310487.6790.68623
10496.7992.7877610508.19 94.310810550.0394.1715610570.8295.2121410601.3395.49726
#Mann= 3 , 0 , 0
9473.171  0.0736       09473.171  0.0736       010601.33  0.0736       0
#XS Ineff= 2 , 0
       09912.957        10075.84       0
Bank Sta=9473.171,10601.33
Exp/Cntr=0.3,0.1

Type RM Length L Ch R = 1 ,17565.53,214.447000,214.447000,214.447000
XS GIS Cut Line= 6
791034.038514674861262.580912352791486.384536207 861179.83005549
791562.899893254 861150.47964932791633.844278067861102.209114209
791809.735120744 860936.88498868792022.723389804860800.196486682
#Sta/Elev= 30
 9477.6489.672959529.44788.934299590.44386.406679742.93276.211289763.26474.40921
9793.76273.705469803.92874.287959844.592 72.92819864.92373.333669957.90271.96071
9968.86567.40948 9979.6860.491919990.20556.4204810000.7155.1856310011.24 58.1224
10021.9267.5085110033.1469.7083210177.6870.5158210233.9471.5137910273.2572.82314
10288.7973.7786910436.0474.1792810471.9775.34359   1047675.5973710487.67 79.1416
10499.3385.30351   10511 90.065710522.67  94.176 10590.795.5302910600.6494.97265
#Mann= 3 , 0 , 0
 9477.64    0.06       0 9477.64    0.06       010600.64    0.06       0
#XS Ineff= 2 , 0
       09932.971        10136.59       0
Bank Sta=9477.64,10600.64
Exp/Cntr=0.3,0.1

Type RM Length L Ch R = 1 ,17351.08,200.306400,200.306400,200.306400
XS GIS Cut Line= 6
 791078.54436633861347.546629116 791665.86376217 861363.65574789
791722.292596251861161.793415129791776.890683293861068.778988898
791900.365702629860953.427704319792078.776428431860843.189610258
#Sta/Elev= 30
9326.31688.233879362.78587.128939432.81181.798329502.83879.117339542.85375.88616
 9722.9274.162139762.93572.826559832.96272.18205 9934.7372.489979955.96565.24977
9966.50764.220529977.04960.932639987.59155.176789998.13254.4221110008.6954.97815
10019.3257.5068710039.5158.70865 10059.764.6985710079.8967.51849 10212.770.08266
10264.4372.95931 10278.172.7318210303.52 73.752410444.4474.0174410456.6275.43753
 10468.882.3321310480.6888.10263 10492.591.0919310515.9594.8659210612.1695.11212
#Mann= 3 , 0 , 0
9326.316    0.04       09326.316    0.04       010612.16    0.04       0
#XS Ineff= 2 , 0
       0                10173.83       0
Bank Sta=9326.316,10612.16
Exp/Cntr=0.3,0.1

Type RM Length L Ch R = 1 ,17150.77,126.233100,126.233100,126.233100
XS GIS Cut Line= 6
791130.015058726861375.261062294791781.864084274861375.469772592
791814.984127283861356.060013577791926.584352046861313.639086634
792212.997052908861182.870732412792416.838074774861100.936628982
#Sta/Elev= 30
9268.256 84.83519313.24181.182229363.24180.172189433.24176.128249753.24172.11199
9893.24173.040169903.24169.377079913.24167.018219940.81265.922759958.51166.10383
9969.20859.845099979.90654.9745710001.2749.8607210011.9753.1221310033.3861.93244
10065.4968.1109710076.19 69.538610098.1369.1927710131.1170.74575 10142.175.90699
 10153.183.3570910164.0985.23258   1029688.2840710405.7488.6811210427.3987.61771
10492.37 79.923510546.22 81.192110573.1981.2106510599.7780.1812810612.4580.61741
#Mann= 3 , 0 , 0
9268.256   0.075       09268.256   0.075       010612.45   0.075       0
#XS Ineff= 2 , 0
       0                               0
Bank Sta=9268.256,10612.45
Exp/Cntr=0.3,0.1

Type RM Length L Ch R = 1 ,17024.54,137.766900,137.766900,137.766900
XS GIS Cut Line= 3
791208.082190394861474.471375436791999.680629164861464.880237997
792168.263400555861280.113520563
#Sta/Elev= 30
9344.48379.864999391.40478.670339411.40677.760989481.41176.416119501.41275.69626
9591.41973.248549701.427  71.1919801.43468.938869891.44167.496829961.44665.86375
10011.4565.2059310031.4565.1592810061.45  65.54810149.5165.4493310163.0565.63885
 10173.771.9487710176.5973.4684310190.1384.5925610203.6685.4008410233.0586.79454
10244.2787.5414110247.8987.4310910257.8187.5837410271.3586.7309310284.8886.63864
10298.4286.6326510311.9687.0462310325.4986.8156210352.5786.7734710386.2687.26282
#Mann= 3 , 0 , 0
9344.483  0.0701       09344.483  0.0701       010386.26  0.0701       0
#XS Ineff= 2 , 0
       0                10079.64       0
Bank Sta=9344.483,10386.26
Exp/Cntr=0.3,0.1

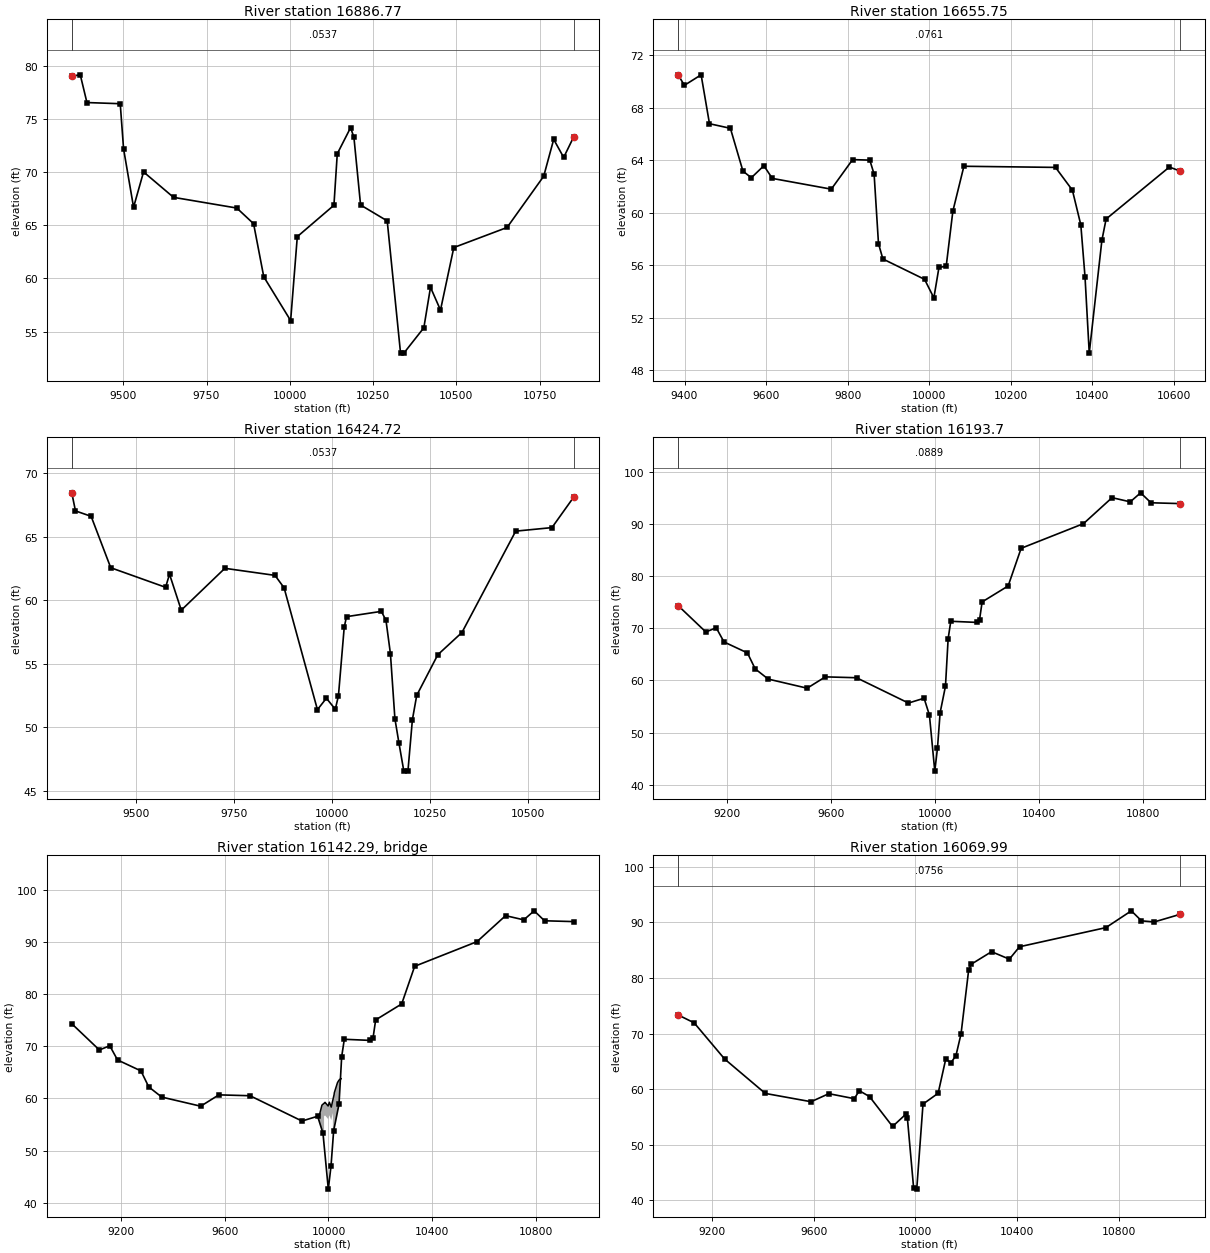
Type RM Length L Ch R = 1 ,16886.77,231.024100,231.024100,231.024100
XS GIS Cut Line= 6
791219.466980398861572.055289984791723.803126246861583.107795939
791826.981653214861600.798700288791859.680228055861603.548413157
791955.844831139861601.986010522792725.512061685 861604.58326149
#Sta/Elev= 30
9345.25779.039759370.79579.15069  9390.876.543119490.82276.434539500.82472.18969
9530.83166.698619560.83870.018639650.85867.628939840.90866.621799891.31665.14738
9921.87260.1594810002.5856.0379410022.5963.93331 10132.666.88539 10142.671.72399
 10182.674.17892 10192.673.2783410212.6166.9097110292.6165.4147610332.6152.99384
10342.6152.9781410402.6155.3618810422.61  59.16910452.6157.0248510492.6162.90772
10652.6164.7955810762.6169.6153610792.6173.0779910822.6171.3825310853.1273.34434
#Mann= 3 , 0 , 0
9345.257  0.0537       09345.257  0.0537       010853.12  0.0537       0
#XS Ineff= 2 , 0
       0                10172.46       0
Bank Sta=9345.257,10853.12
Exp/Cntr=0.3,0.1

Type RM Length L Ch R = 1 ,16655.75,231.024200,231.024200,231.024200
XS GIS Cut Line= 6
791260.330443558861971.233278215791728.702868478 861849.69801538
791819.906535073861809.054346007791856.891713787861759.077114104
791886.744529292861741.798619867792420.958091615861615.403645654
#Sta/Elev= 30
9384.49170.498319399.54169.708619440.57770.509549461.09566.78623 9512.3966.43512
9543.16763.175189563.68562.670589594.49263.587469615.08962.620049759.744 61.8013
9812.03764.053249854.22764.011839864.77462.937589875.46757.655829886.24756.48418
9988.49654.9322110011.2553.5213810023.7755.8440710041.48 55.923610057.85 60.1289
10084.89 63.545410309.5363.4588710350.8961.7252310371.5759.08202 10381.955.11225
10392.2449.3127510423.2657.91254 10433.659.5282610588.6863.4856810615.5263.17538
#Mann= 3 , 0 , 0
9384.491  0.0761       09384.491  0.0761       010615.52  0.0761       0
#XS Ineff= 2 , 0
       0                10210.79       0
Bank Sta=9384.491,10615.52
Exp/Cntr=0.3,0.1

Type RM Length L Ch R = 1 ,16424.72,231.024100,231.024100,231.024100
XS GIS Cut Line= 6
791325.574961841862068.972607315791662.945231497862075.528090149
791729.955839783 862060.65360491791837.812460959 862019.51903832
792153.014899075861831.680767998792529.448535293861723.612107933
#Sta/Elev= 30
9335.52668.472739344.95267.04913 9384.9666.621979434.96962.573359574.996 61.0308
9584.99862.063489615.00359.229449726.281 62.52699854.19461.97102 9877.4660.99002
9962.53851.394579985.40652.2920410008.1551.4252410016.1752.4867710030.9157.88407
10036.7458.71856 10125.759.1359410137.4758.4326610148.8755.7998410160.2750.68348
10170.6248.7632410182.8446.5928410193.5446.5515510204.9450.6061410215.9952.51917
10269.7855.7198810331.3857.4704710468.6165.4547510561.1565.7333910617.0168.15118
#Mann= 3 , 0 , 0
9335.526  0.0537       09335.526  0.0537       010617.01  0.0537       0
#XS Ineff= 2 , 0
       0                10067.11       0
Bank Sta=9335.526,10617.01
Exp/Cntr=0.3,0.1

Type RM Length L Ch R = 1 , 16193.7,123.706400,123.706400,123.706400
XS GIS Cut Line= 6
791108.871877253862134.789197221791417.898476332862122.602549538
792048.579304963862118.861119941 792149.72084108862094.078094542
 792308.46616593862077.332807109 793037.78058821862090.876435682
#Sta/Elev= 30
9011.57174.297159117.78269.270749157.81370.073089187.83667.354329277.90665.25774
 9307.9362.195839357.94360.242869507.95658.493899577.96260.666419697.969 60.4993
9897.96955.650719958.15956.570089978.75153.334889999.34342.6041510009.6446.96193
10019.9353.8015210040.5358.8796210050.8267.9916410060.9971.3167810161.5571.10143
 10171.671.5685610181.6675.0278710281.8578.0873810331.8685.30058 10571.990.02546
10681.9295.0049610751.93 94.201110791.9495.9303410831.9594.0234210944.75 93.8658
#Mann= 3 , 0 , 0
9011.571  0.0889       09011.571  0.0889       010944.75  0.0889       0
#XS Ineff= 2 , 0
       0                               0
Bank Sta=9011.571,10944.75
Exp/Cntr=0.3,0.1

Type RM Length L Ch R = 3 ,16142.29,,,
BEGIN DESCRIPTION:
END DESCRIPTION:
Bridge Culvert--1,0,-1,-1, 0
Deck Dist Width WeirC Skew NumUp NumDn MinLoCord MaxHiCord MaxSubmerge Is_Ogee
46.853200,30.000000,2.6,0, 19, 19, , , 0.95, 0, 0,0,,
 9956.55 9962.84 9966.88 9974.78 9983.00 9983.00 9985.15 9986.73 9998.6810003.42
10010.6310017.0010017.0010021.7010022.5810034.5210039.9710046.4710048.95
   56.45   56.34   57.16   58.70   59.06   59.06   59.15   59.24   58.53   59.26
   58.32   59.72   59.72   60.75   61.10   63.00   63.46   63.75   63.76
 -943.55 -943.66 -942.84 -941.30 -940.94   56.56   56.65   56.74   56.03   56.76
   55.82   57.22 -940.28 -939.25 -938.90 -937.00 -936.54 -936.25 -936.24
 9956.55 9962.84 9966.88 9974.78 9983.00 9983.00 9985.15 9986.73 9998.6810003.42
10010.6310017.0010017.0010021.7010022.5810034.5210039.9710046.4710048.95
   56.45   56.34   57.16   58.70   59.06   59.06   59.15   59.24   58.53   59.26
   58.32   59.72   59.72   60.75   61.10   63.00   63.46   63.75   63.76
 -943.55 -943.66 -942.84 -941.30 -940.94   56.56   56.65   56.74   56.03   56.76
   55.82   57.22 -940.28 -939.25 -938.90 -937.00 -936.54 -936.25 -936.24
BR Coef=-1 , 0 , 0 ,, 0 ,,,0.8,0,1,0,
WSPro=,,,, 1 ,,,, 0 ,,,, 0 ,,,,-1 ,-1 ,-1 , 0 , 0 , 0 , 0 , 0
BC Design=,, 0 ,, 0 ,,,,,,

Type RM Length L Ch R = 1 ,16069.99,207.101600,207.101600,207.101600
XS GIS Cut Line= 6
 791102.36628294862191.713147387 791913.94719401862182.493212193
 792000.35287714862163.738490269 792053.93779695 862238.08756648
792305.901229113862225.867517486 793037.78058821862219.361923188
#Sta/Elev= 30
9067.337 73.35249129.97671.940669249.986  65.4359410.01259.249149590.051 57.7602
9660.05159.206039760.052 58.30789780.05359.737929820.05558.684749910.78153.30773
9961.94555.466769968.97854.901299993.63142.2899310005.9642.0439310030.6157.33574
10090.1759.28053 10120.265.4473810140.2364.7559910160.2566.0418410180.2769.95259
10210.3181.4433810220.3282.4793410300.4284.7341610370.4383.3928310410.4385.62173
10750.4589.0637610850.4592.0819110890.4590.2846310940.4590.0803111043.24 91.4614
#Mann= 3 , 0 , 0
9067.337  0.0756       09067.337  0.0756       011043.24  0.0756       0
#XS Ineff= 2 , 0
       0                               0
Bank Sta=9067.337,11043.24
Exp/Cntr=0.3,0.1

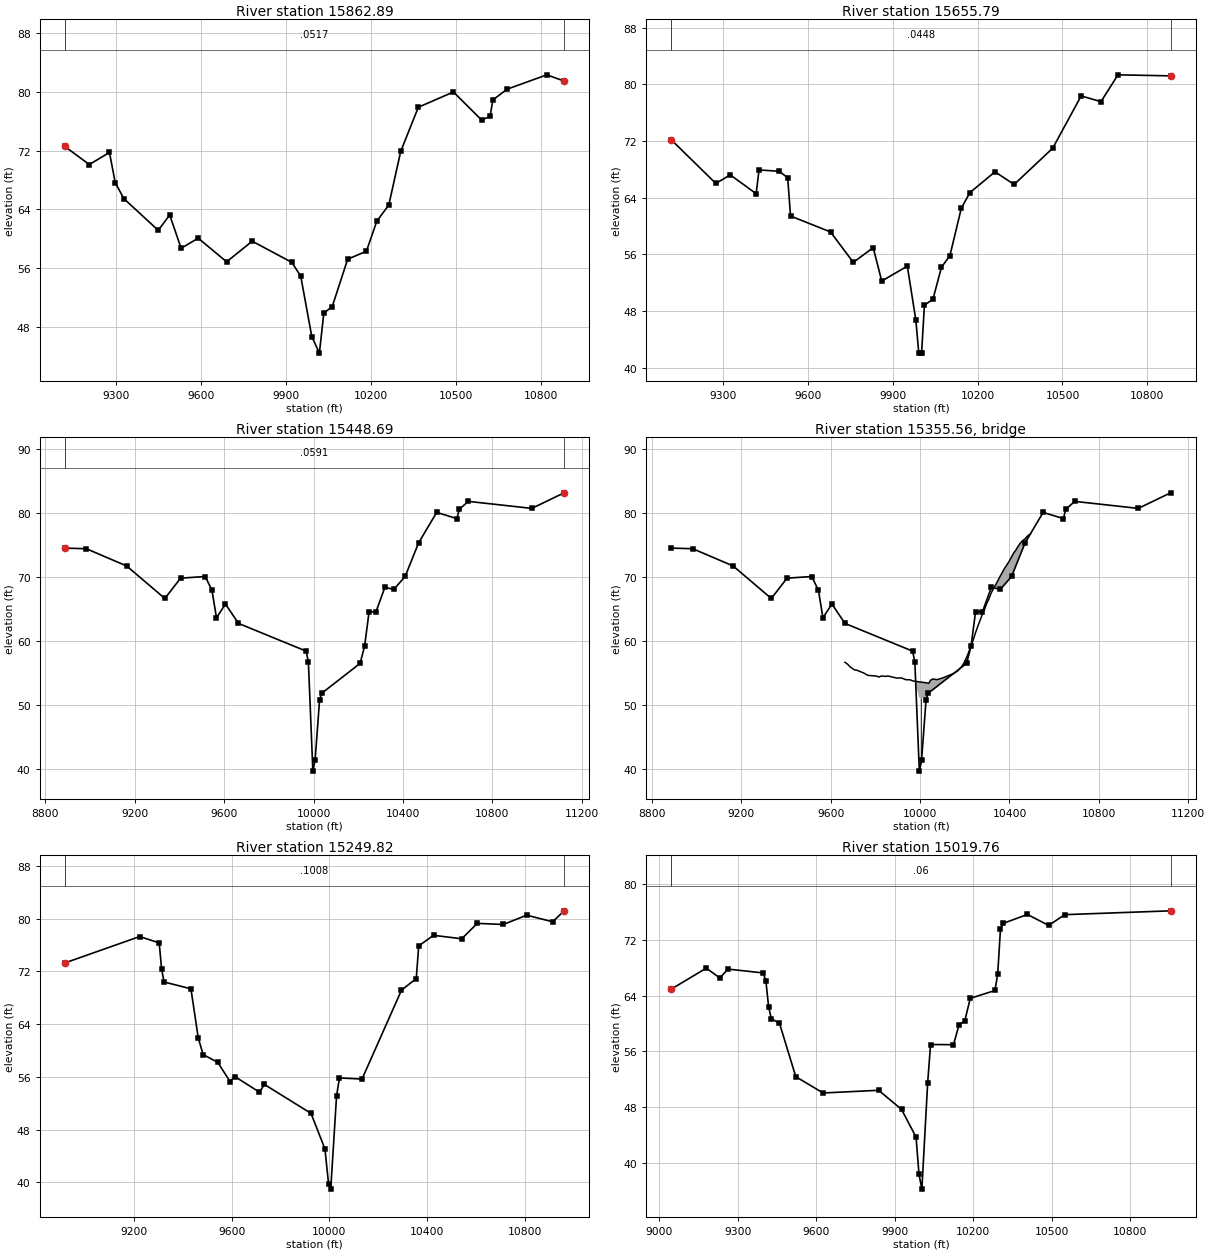
Type RM Length L Ch R = 1 ,15862.89,207.101700,207.101700,207.101700
XS GIS Cut Line= 6
791039.901332997862311.417463106 791689.48422507862244.672286385
791821.103370851862281.163944614791992.173307862862410.675847252
792184.709300619862485.660709361792725.967455764862529.220546532
#Sta/Elev= 30
9120.06472.572099206.51170.11159 9277.6271.747439297.93767.638249328.36865.46483
9449.62161.145489489.92963.246999530.159 58.70549590.39260.080239690.47456.86544
9780.70459.669899920.24756.79174 9951.7254.906719990.61946.6945510017.3944.43447
10033.0649.8859410062.7650.7735410117.0257.2173210183.2358.3081610219.7462.39599
10261.9764.5902610304.0871.9029710366.1877.9075810489.8979.9857110588.8376.17892
10618.87 76.653310628.8978.9018910678.95 80.364410818.9882.3189810879.9581.47016
#Mann= 3 , 0 , 0
9120.064  0.0517       09120.064  0.0517       010879.95  0.0517       0
#XS Ineff= 2 , 0
       09901.201                       0
Bank Sta=9120.064,10879.95
Exp/Cntr=0.3,0.1

Type RM Length L Ch R = 1 ,15655.79,207.101600,207.101600,207.101600
XS GIS Cut Line= 6
790980.264370385862652.688613202791430.142150462862572.525522132
791902.498156537862523.893368353791993.222562411862527.046681921
792351.751058791862574.173450049792730.806674184862576.354425877
#Sta/Elev= 30
9118.10472.185099275.64466.00842 9326.55  67.2249418.03764.561289428.16367.91532
9499.03967.733089529.41566.81939 9539.5461.408949680.73759.158389761.20854.86116
9831.48656.941629861.60552.220689952.02754.32992 9982.2146.666289992.27242.12035
    999942.0405710002.34 42.050610012.3848.80711 10042.549.6595910072.5354.16633
10102.5455.8261610142.6762.5173910173.0164.7136610261.8167.6556710329.1765.86279
 10465.770.9988310565.9378.3711910635.98 77.566110695.9981.3538310881.8681.20736
#Mann= 3 , 0 , 0
9118.104  0.0448       09118.104  0.0448       010881.86  0.0448       0
#XS Ineff= 2 , 0
       09951.353         10110.3       0
Bank Sta=9118.104,10881.86
Exp/Cntr=0.3,0.1

Type RM Length L Ch R = 1 ,15448.69,198.869400,198.869400,198.869400
XS GIS Cut Line= 6
790768.954574883862651.983944371791543.120296985862721.919083133
791830.737396449 862739.36842297791992.036094427862722.682782754
792557.993008345862651.983944371792974.351043791862521.872058287
#Sta/Elev= 30
8886.72674.585818983.16274.487429163.89571.789259334.58766.710419404.87269.88953
 9515.3270.144929545.44267.988999565.52463.691579605.68765.851039664.04462.81638
9966.54958.486539976.61756.839379996.75239.73099 10006.841.47876 10026.950.92113
10036.9551.9158410208.0456.56705 10228.259.2586510248.3564.6552310278.5864.57909
 10318.968.4498510359.2168.13719 10409.670.1608810470.0675.4142210550.6880.16653
10641.38  79.19410651.4680.6310910692.0581.8892510976.3380.7916111120.9283.22496
#Mann= 3 , 0 , 0
8886.726  0.0591       08886.726  0.0591       011120.92  0.0591       0
#XS Ineff= 2 , 0
       0                10104.89       0
Bank Sta=8886.726,11120.92
Exp/Cntr=0.3,0.1

Type RM Length L Ch R = 3 ,15355.56,,,
BEGIN DESCRIPTION:
END DESCRIPTION:
Bridge Culvert--1,0,-1,-1, 0
Deck Dist Width WeirC Skew NumUp NumDn MinLoCord MaxHiCord MaxSubmerge Is_Ogee
87.934700,23.000000,2.6,0, 53, 53, , , 0.95, 0, 0,0,,
 9663.90 9676.15 9686.16 9706.17 9716.18 9746.20 9766.22 9806.25 9816.26 9826.27
 9846.28 9856.29 9896.32 9916.33 9936.34 9956.35 9965.86 9980.90 9980.9010025.90
10025.9010039.6710046.3910056.3910076.4010106.4110146.4310166.4610186.6110196.68
10206.7610217.3110236.9910247.0610257.1410277.2910287.3710297.4410307.5210317.60
10327.6710337.7510357.9010378.0510398.2010418.3610428.5810438.8210449.0610459.29
10469.5310479.7710494.50
   56.75   56.43   56.05   55.56   55.51   55.10   54.70   54.58   54.43   54.60
   54.54   54.60   54.27   54.30   54.02   54.00   53.84   53.76   53.76   53.54
   53.54   53.47   53.92   54.13   54.03   54.36   54.94   55.33   56.09   56.66
   57.39   58.28   60.14   61.25   62.25   64.11   64.90   65.87   66.60   67.52
   68.24   68.80   70.16   71.42   72.50   73.80   74.28   74.87   75.38   75.77
   76.03   76.44   76.83
 -943.25 -943.57 -943.95 -944.44 -944.49 -944.90 -945.30 -945.42 -945.57 -945.40
 -945.46 -945.40 -945.73 -945.70 -945.98 -946.00 -946.16 -946.24   51.26   51.04
 -946.46 -946.53 -946.08 -945.87 -945.97 -945.64 -945.06 -944.67 -943.91 -943.34
 -942.61 -941.72 -939.86 -938.75 -937.75 -935.89 -935.10 -934.13 -933.40 -932.48
 -931.76 -931.20 -929.84 -928.58 -927.50 -926.20 -925.72 -925.13 -924.62 -924.23
 -923.97 -923.56 -923.17
 9663.90 9676.15 9686.16 9706.17 9716.18 9746.20 9766.22 9806.25 9816.26 9826.27
 9846.28 9856.29 9896.32 9916.33 9936.34 9956.35 9965.86 9983.68 9983.6810028.68
10028.6810039.6710046.3910056.3910076.4010106.4110146.4310166.4610186.6110196.68
10206.7610217.3110236.9910247.0610257.1410277.2910287.3710297.4410307.5210317.60
10327.6710337.7510357.9010378.0510398.2010418.3610428.5810438.8210449.0610459.29
10469.5310479.7710494.50
   56.75   56.43   56.05   55.56   55.51   55.10   54.70   54.58   54.43   54.60
   54.54   54.60   54.27   54.30   54.02   54.00   53.84   53.75   53.75   53.52
   53.52   53.47   53.92   54.13   54.03   54.36   54.94   55.33   56.09   56.66
   57.39   58.28   60.14   61.25   62.25   64.11   64.90   65.87   66.60   67.52
   68.24   68.80   70.16   71.42   72.50   73.80   74.28   74.87   75.38   75.77
   76.03   76.44   76.83
 -943.25 -943.57 -943.95 -944.44 -944.49 -944.90 -945.30 -945.42 -945.57 -945.40
 -945.46 -945.40 -945.73 -945.70 -945.98 -946.00 -946.16 -946.25   51.25   51.02
 -946.48 -946.53 -946.08 -945.87 -945.97 -945.64 -945.06 -944.67 -943.91 -943.34
 -942.61 -941.72 -939.86 -938.75 -937.75 -935.89 -935.10 -934.13 -933.40 -932.48
 -931.76 -931.20 -929.84 -928.58 -927.50 -926.20 -925.72 -925.13 -924.62 -924.23
 -923.97 -923.56 -923.17
Pier Skew, UpSta & Num, DnSta & Num=  ,10003.40, 2 ,10006.18, 2 , 0 , 0 , 0 ,,
    2.00    2.00
 -946.35   53.65
    2.00    2.00
 -946.36   53.64
BR Coef=-1 , 0 , 0 ,, 0 ,,,0.8,0,1,0,
WSPro=,,,, 1 ,,,, 0 ,,,, 0 ,,,,-1 ,-1 ,-1 , 0 , 0 , 0 , 0 , 0
BC Design=,, 0 ,, 0 ,,,,,,

Type RM Length L Ch R = 1 ,15249.82,230.061700,230.061700,230.061700
XS GIS Cut Line= 6
790858.406496584862889.438136429791517.097919822862918.713310793
791877.649236679 862956.55847311791974.642870307862894.345462769
792374.209969252862837.393382013792849.118353456862663.368734404
#Sta/Elev= 30
8915.46273.266639222.35877.274069302.43776.314769312.44772.316989322.45770.38231
9432.56669.347739462.59561.874469482.61559.368869542.674 58.19199592.80455.28655
9612.91456.032329713.46453.665339733.57354.846279924.61750.455789981.76145.06234
9996.63239.7441210005.5538.9659610029.2753.0668210041.1355.8284210133.7455.66032
10295.3569.1379410355.9670.9063110366.0675.8594710426.6777.4608310542.2276.93787
10606.12 79.273310712.6279.1074210808.47 80.515810914.9879.5144310961.9681.17554
#Mann= 3 , 0 , 0
8915.462  0.1008       08915.462  0.1008       010961.96  0.1008       0
#XS Ineff= 2 , 0
       09927.891                       0
Bank Sta=8915.462,10961.96
Exp/Cntr=0.3,0.1

Type RM Length L Ch R = 1 ,15019.76,230.061700,230.061700,230.061700
XS GIS Cut Line= 6
791145.393296837863407.374056963791778.825603291863232.125913767
792168.471823112863065.057409454792332.275148515863010.614030449
792558.496199253862962.337524764792974.979398297862899.878780515
#Sta/Elev= 30
9046.57464.93537 9180.59 67.94069232.29166.531329263.31267.802249397.73567.25532
9408.07566.093289418.41562.410289428.75560.687099459.79960.060869522.18352.39325
9626.53750.058399838.62550.442469925.90847.711749981.45843.741449992.572 38.4277
10003.6636.2855410025.8151.5284110036.8957.00173 10124.456.97455 10145.859.85081
10167.1360.3295610188.4563.6159410282.8364.7379310293.2767.1310810303.6873.48312
10313.9774.3462610406.4975.6317710487.9674.0612910548.9675.60126 10953.476.15041
#Mann= 3 , 0 , 0
9046.574    0.06       09046.574    0.06       0 10953.4    0.06       0
#XS Ineff= 2 , 0
       0                               0
Bank Sta=9046.574,10953.4
Exp/Cntr=0.3,0.1