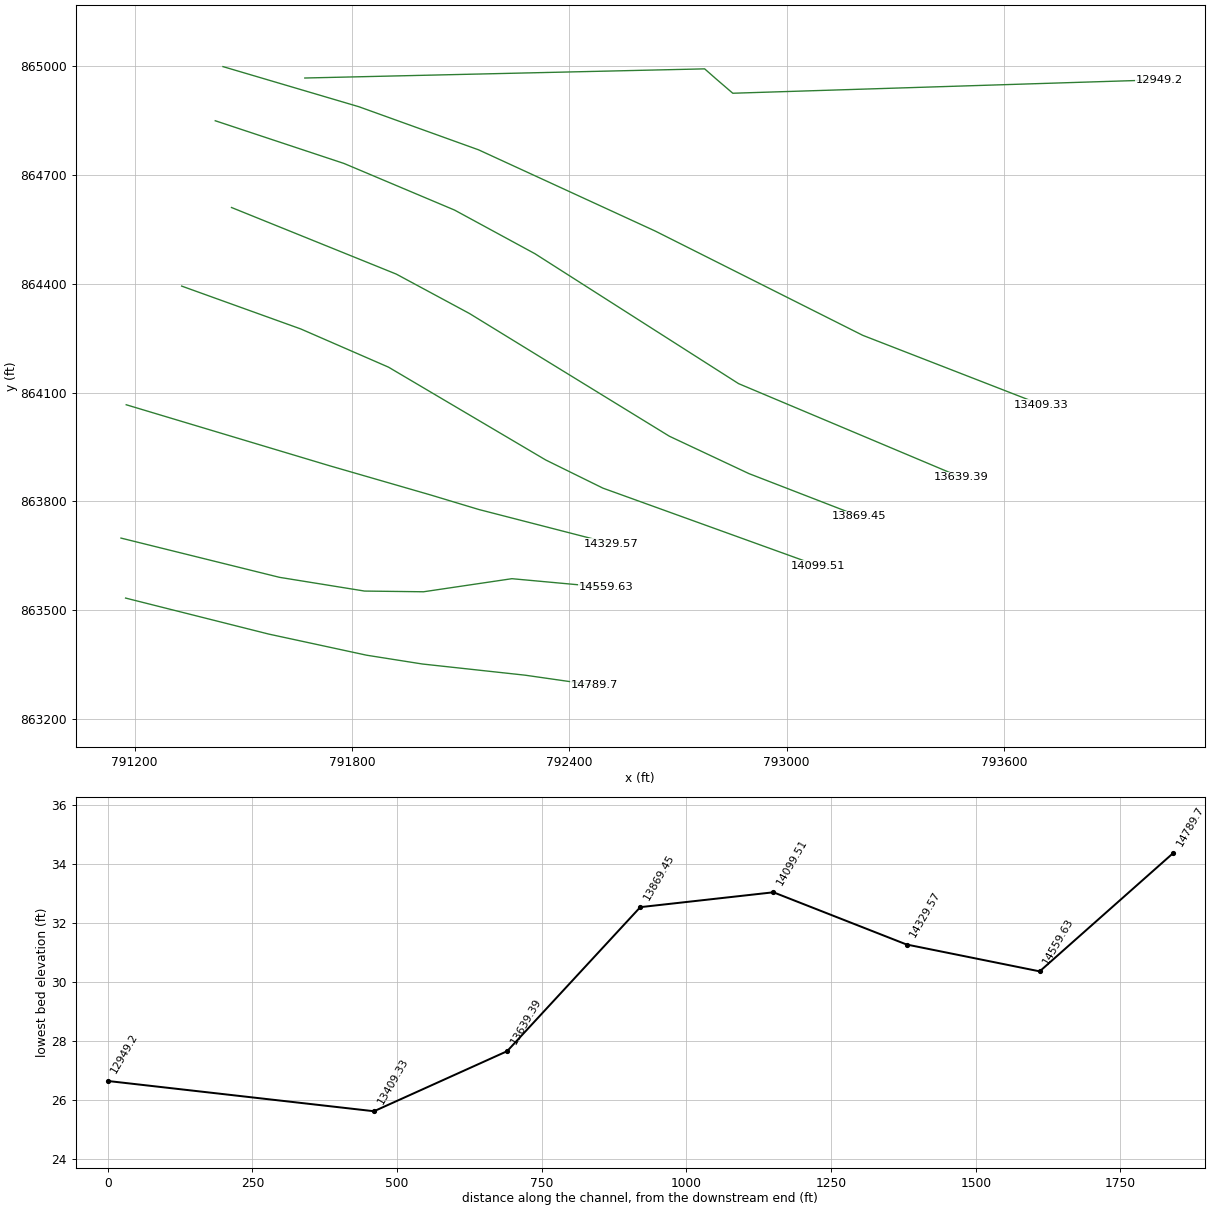
HEC-RAS study 16165_ras.prj: 16165

--- 16165_ras.g01 (geometry) --- (continued)

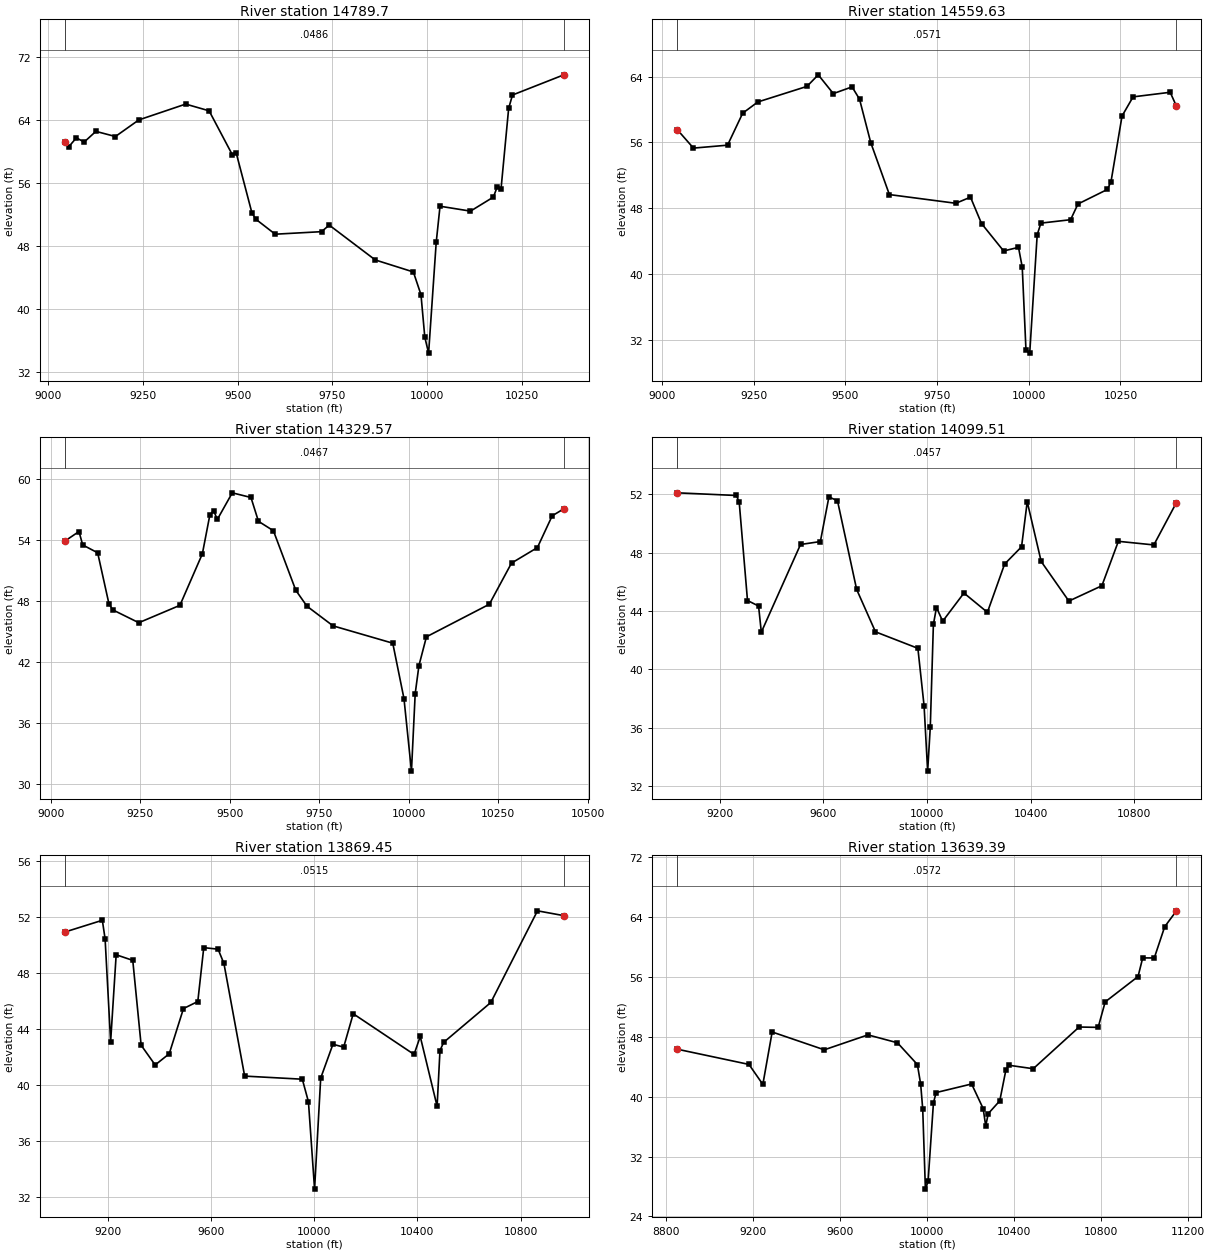
Type RM Length L Ch R = 1 , 14789.7,230.061700,230.061700,230.061700
XS GIS Cut Line= 6
791175.253265572863533.332414404791570.265486358863434.016998895
791840.850624134863375.656751484791994.682263099863351.410798332
792278.238443096  863320.5762643792469.230731499863293.221375961
#Sta/Elev= 30
9043.49761.202159053.547 60.5464 9074.1761.704459094.79261.172569125.72662.53024
9177.28261.875589239.149 63.98489362.88465.996779424.75165.141819486.42559.52718
 9496.68 59.72159537.70252.192539547.95751.373619599.23449.462079721.66849.78365
9741.98750.618729863.49746.191959964.18444.663769984.30641.775349994.36636.38017
10004.4234.3491610024.5448.43811 10034.653.0160510115.0652.3938310175.4454.17575
10185.5455.4533210195.6455.1713310215.84 65.449610225.9567.1493810361.5569.71452
#Mann= 3 , 0 , 0
9043.497  0.0486       09043.497  0.0486       010361.55  0.0486       0
#XS Ineff= 2 , 0
       0                               0
Bank Sta=9043.497,10361.55
Exp/Cntr=0.3,0.1

Type RM Length L Ch R = 1 ,14559.63,230.061700,230.061700,230.061700
XS GIS Cut Line= 6
 791162.52706103863698.786714426 791600.14757844863590.510388879
791834.979613532863552.634818778791997.786513097 863550.68026849
792241.818059083 863586.77144435792501.877359039863562.910907629
#Sta/Elev= 30
9042.11757.529699085.96455.299069178.87755.655879220.17259.552319261.46760.91473
9395.32962.809749426.11464.216519467.15961.932099518.266 62.74869538.62861.25622
9569.17155.971789620.02449.643949801.07648.58512 9841.1149.329599871.12546.12316
9931.43442.782259971.96343.221119982.16440.823469992.36530.7028510002.5730.35021
10022.9444.7546610033.1246.1713610114.0146.5857710134.0548.4965810214.0950.26579
 10224.151.2005610254.1959.2033710284.3361.5346910385.4662.0925510402.5860.39434
#Mann= 3 , 0 , 0
9042.117  0.0571       09042.117  0.0571       010402.58  0.0571       0
#XS Ineff= 2 , 0
       0                               0
Bank Sta=9042.117,10402.58
Exp/Cntr=0.3,0.1

Type RM Length L Ch R = 1 ,14329.57,230.061800,230.061800,230.061800
XS GIS Cut Line= 6
791176.964624746864066.615350254791738.312903208863898.343099181
792016.766696577863817.913175138792098.968113128 863793.13469818
792150.626617995863777.612332736792516.474175423863683.493303763
#Sta/Elev= 30
9039.28153.849539078.98954.793339089.42953.476599131.18752.707649162.506 47.7244
9172.94647.107539246.02345.838349360.85947.547199423.49752.605219444.376 56.4149
9454.81656.855519465.255 55.98089507.01458.596359559.21258.138329580.09155.79954
 9621.8554.872329684.31349.026059715.53947.460089788.40145.528969955.07843.82781
9986.41138.38307 10007.331.2608410017.7438.8780510028.1841.6275510049.0744.45296
10224.6747.6513910286.6251.69325 10358.953.21771 10400.256.33819 10432.757.02658
#Mann= 3 , 0 , 0
9039.281  0.0467       09039.281  0.0467       0 10432.7  0.0467       0
#XS Ineff= 2 , 0
       09547.151                       0
Bank Sta=9039.281,10432.7
Exp/Cntr=0.3,0.1

Type RM Length L Ch R = 1 ,14099.51,230.061700,230.061700,230.061700
XS GIS Cut Line= 6
  791329.9684622864393.983062617791658.928498808864275.674522305
791901.085650062864170.329330974792335.269199183863914.182302421
792493.133863512863836.546802988793087.955057348863622.016655512
#Sta/Elev= 30
9036.58652.093719264.57951.910659275.256 51.45929307.28444.717469349.98944.34085
9360.66542.548649511.96948.554369588.60848.756129621.62451.812879654.71851.54983
9728.64445.477939801.37242.572349965.08941.443539989.05637.50024 10002.833.03096
   1001336.0501410024.9743.0796410036.9444.2374710060.8743.2993910142.9345.22987
10233.5343.9088110299.9247.2141310365.3548.3977310387.2451.4835710441.0947.39188
10548.0144.6793510675.5145.7294610739.1148.7721510876.1148.5250310963.4251.43032
#Mann= 3 , 0 , 0
9036.586  0.0457       09036.586  0.0457       010963.42  0.0457       0
#XS Ineff= 2 , 0
       09599.294        10396.29       0
Bank Sta=9036.586,10963.42
Exp/Cntr=0.3,0.1

Type RM Length L Ch R = 1 ,13869.45,230.061700,230.061700,230.061700
XS GIS Cut Line= 6
791467.696767225   864610.743223791922.499131417 864427.07467728
 792124.48202327864318.387398113  792676.5555591863979.752059883
792896.172845613863876.656945551793199.340469085863759.392398292
#Sta/Elev= 30
9032.081 50.90359177.88151.747139188.61150.416059210.07143.072369231.53149.28096
 9295.9148.88105 9328.3842.815669382.76741.40397 9437.3342.203329492.518 45.4345
9548.15345.938169571.27549.790399626.80849.680799649.49648.659879729.90740.60762
9953.56640.385029977.33938.7715410001.1132.5274110024.8540.4640610072.33 42.8842
10113.92 42.677510151.0545.0641710387.0142.1570710410.9643.4398310476.3938.45032
10487.5342.4374110501.8243.0195210684.7745.87044 10865.752.4222710967.91 52.0774
#Mann= 3 , 0 , 0
9032.081  0.0515       09032.081  0.0515       010967.91  0.0515       0
#XS Ineff= 2 , 0
       09589.631        10222.75       0
Bank Sta=9032.081,10967.91
Exp/Cntr=0.3,0.1

Type RM Length L Ch R = 1 ,13639.39,230.061700,230.061700,230.061700
XS GIS Cut Line= 6
791422.783645923864850.065001842791778.223811777864732.247666436
792083.427440696864603.665224472 792305.61585192864483.138143273
792867.492750431864124.894592325793480.923822924863866.849753601
#Sta/Elev= 30
8854.15346.352519182.83444.320749246.59441.647089289.36748.657599528.72846.27541
9729.16648.270869864.69747.214589956.18644.304689971.33141.673279980.71938.35233
9992.98527.64439 10005.3 28.684510029.9339.1672110042.24 40.557410205.2541.70556
10258.26 38.417710269.9736.1011110281.6837.7431510334.4439.4488210362.7743.59904
 10375.944.2114310488.1443.7449210698.8749.3227210786.2249.2738310818.6452.68406
10969.4256.0728310990.8258.5651811044.02 58.5579 11091.862.7344311145.8664.86066
#Mann= 3 , 0 , 0
8854.153  0.0572       08854.153  0.0572       011145.86  0.0572       0
#XS Ineff= 2 , 0
       09551.354        10192.21       0
Bank Sta=8854.153,11145.86
Exp/Cntr=0.3,0.1

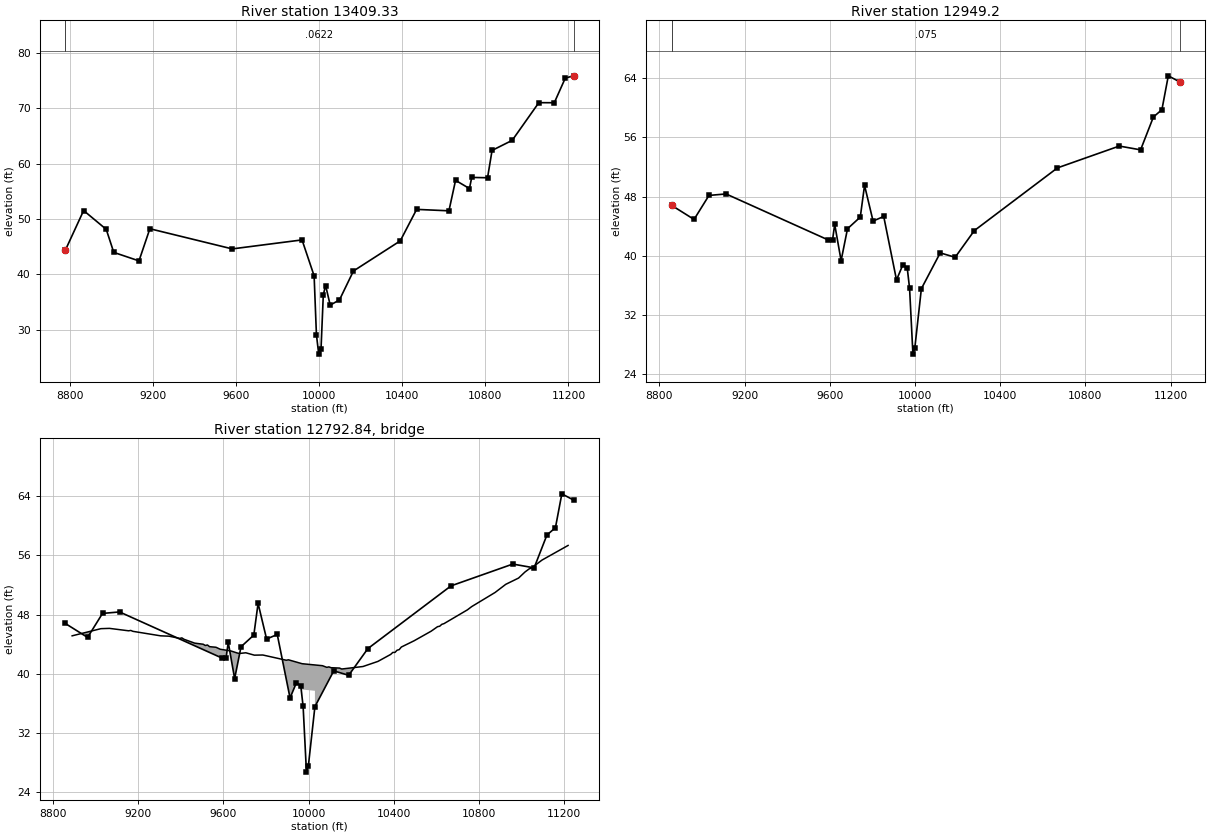
Type RM Length L Ch R = 1 ,13409.33,460.123400,460.123400,460.123400
XS GIS Cut Line= 6
791444.079711714864999.429665537791819.292131591864888.759804095
792149.732897859864769.861161925792637.363293834864545.832196529
793210.506340354864258.064162349793702.532248754864066.997555864
#Sta/Elev= 30
8775.71444.329968864.44951.545598973.41848.147419009.54743.990219131.04942.45241
9183.51448.259339580.26844.618569916.52846.241849974.71939.753899985.76729.15078
9996.81525.6081710007.9226.48587   1001936.3557710030.0837.9994510052.24 34.4584
10096.9335.4087810164.0940.6258510389.5846.06423 10468.551.7568410624.0851.49722
10656.0157.0024310722.9655.5218810733.8557.5306910810.0857.4696210831.8762.40811
10928.9164.2297111057.1671.0366111131.6671.0237211184.5875.47354 11224.375.88427
#Mann= 3 , 0 , 0
8775.714  0.0622       08775.714  0.0622       0 11224.3  0.0622       0
#XS Ineff= 2 , 0
       09516.558                       0
Bank Sta=8775.714,11224.3
Exp/Cntr=0.3,0.1

Type RM Length L Ch R = 1 , 12949.2,300.000000,300.000000,300.000000
XS GIS Cut Line= 6
791669.979385912864967.975516409792773.934459448864993.203426495
 792801.62081039864968.910994306792803.085059077864967.548652306
792851.551690996 864925.97002472794029.883719504864963.096320674
#Sta/Elev= 30
8857.92446.793138962.97244.89217 9032.9948.146169113.01148.347589593.13642.10472
9613.14242.157869623.14444.216839653.15239.30459 9683.1643.629559743.176 45.2113
9763.18149.508189803.19144.673249853.204 45.2929 9913.2236.686389943.22838.76214
9963.58538.303519974.60535.533989990.19226.63415    999927.4328910029.8735.50346
10118.3340.3593110188.3739.7572310278.4143.3764810668.6151.8801610958.7554.83784
 11058.854.3231911118.8358.7726211158.8559.7701611188.8664.3572911243.7763.51789
#Mann= 3 , 0 , 0
8857.924   0.075       08857.924   0.075       011243.77   0.075       0
#XS Ineff= 2 , 0
       0                               0
Bank Sta=8857.924,11243.77
Exp/Cntr=0.3,0.1

Type RM Length L Ch R = 3 ,12792.84,,,
BEGIN DESCRIPTION:
END DESCRIPTION:
Bridge Culvert--1,0,-1,-1, 0
Deck Dist Width WeirC Skew NumUp NumDn MinLoCord MaxHiCord MaxSubmerge Is_Ogee
94.500000,111.000000,2.6,0, 60, 60, , , 0.95, 0, 0,0,,
 8890.53 9025.53 9065.54 9155.54 9165.54 9175.54 9305.54 9345.54 9395.54 9405.54
 9415.54 9465.54 9505.54 9515.55 9525.55 9535.55 9565.55 9585.55 9635.55 9665.55
 9675.55 9705.55 9745.55 9785.55 9895.55 9905.55 9970.00 9970.0010030.0010030.00
10065.5610085.5610095.5610105.5610145.5610155.5610255.5610325.5610385.5610395.56
10405.5610415.5610425.5610435.5610495.5710575.5710605.5710615.5710625.5810635.58
10745.6610765.6710875.7510925.6510985.8311015.8511035.8611045.8711095.9011218.18
   45.11   46.08   46.12   45.79   45.84   45.72   45.11   45.06   44.76   44.83
   44.64   44.12   43.97   43.80   43.87   43.64   43.56   43.29   43.06   42.78
   42.72   42.81   42.49   42.51   41.80   41.86   41.33   41.33   41.16   41.16
   41.06   40.84   40.90   40.79   40.74   40.61   40.95   41.64   42.59   42.86
   42.86   43.16   43.24   43.59   44.44   45.74   46.35   46.41   46.67   46.76
   48.63   49.07   50.99   52.09   52.94   53.76   54.19   54.29   55.38   57.36
 -954.89 -953.92 -953.88 -954.21 -954.16 -954.28 -954.89 -954.94 -955.24 -955.17
 -955.36 -955.88 -956.03 -956.20 -956.13 -956.36 -956.44 -956.71 -956.94 -957.22
 -957.28 -957.19 -957.51 -957.49 -958.20 -958.14 -958.67   37.83   37.66 -958.84
 -958.94 -959.16 -959.10 -959.21 -959.26 -959.39 -959.05 -958.36 -957.41 -957.14
 -957.14 -956.84 -956.76 -956.41 -955.56 -954.26 -953.65 -953.59 -953.33 -953.24
 -951.37 -950.93 -949.01 -947.91 -947.06 -946.24 -945.81 -945.71 -944.62 -942.64
 8890.53 9025.53 9065.54 9155.54 9165.54 9175.54 9305.54 9345.54 9395.54 9405.54
 9415.54 9465.54 9505.54 9515.55 9525.55 9535.55 9565.55 9585.55 9635.55 9665.55
 9675.55 9705.55 9745.55 9785.55 9895.55 9905.55 9970.00 9970.0010030.0010030.00
10065.5610085.5610095.5610105.5610145.5610155.5610255.5610325.5610385.5610395.56
10405.5610415.5610425.5610435.5610495.5710575.5710605.5710615.5710625.5810635.58
10745.6610765.6710875.7510925.6510985.8311015.8511035.8611045.8711095.9011218.18
   45.11   46.08   46.12   45.79   45.84   45.72   45.11   45.06   44.76   44.83
   44.64   44.12   43.97   43.80   43.87   43.64   43.56   43.29   43.06   42.78
   42.72   42.81   42.49   42.51   41.80   41.86   41.33   41.33   41.16   41.16
   41.06   40.84   40.90   40.79   40.74   40.61   40.95   41.64   42.59   42.86
   42.86   43.16   43.24   43.59   44.44   45.74   46.35   46.41   46.67   46.76
   48.63   49.07   50.99   52.09   52.94   53.76   54.19   54.29   55.38   57.36
 -954.89 -953.92 -953.88 -954.21 -954.16 -954.28 -954.89 -954.94 -955.24 -955.17
 -955.36 -955.88 -956.03 -956.20 -956.13 -956.36 -956.44 -956.71 -956.94 -957.22
 -957.28 -957.19 -957.51 -957.49 -958.20 -958.14 -958.67   37.83   37.66 -958.84
 -958.94 -959.16 -959.10 -959.21 -959.26 -959.39 -959.05 -958.36 -957.41 -957.14
 -957.14 -956.84 -956.76 -956.41 -955.56 -954.26 -953.65 -953.59 -953.33 -953.24
 -951.37 -950.93 -949.01 -947.91 -947.06 -946.24 -945.81 -945.71 -944.62 -942.64
BR Coef=-1 , 0 , 0 ,, 0 ,,,0.8,0,1,0,
WSPro=,,,, 1 ,,,, 0 ,,,, 0 ,,,,-1 ,-1 ,-1 , 0 , 0 , 0 , 0 , 0
BC Design=,, 0 ,, 0 ,,,,,,