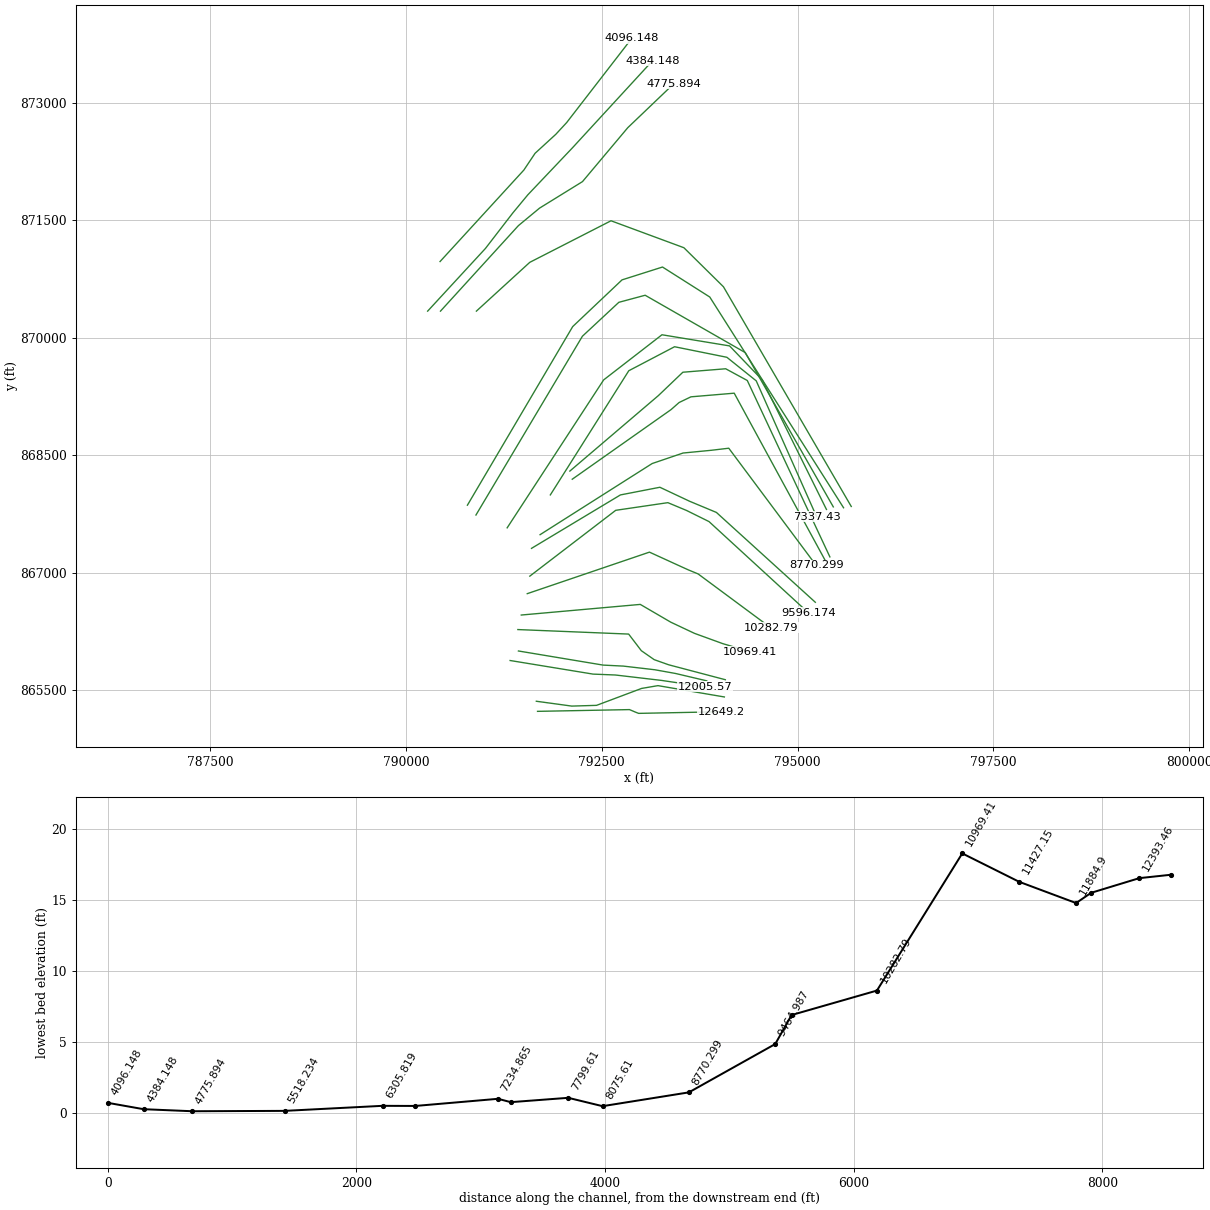
HEC-RAS study 16165_ras.prj: 16165

--- 16165_ras.g01 (geometry) --- (continued)

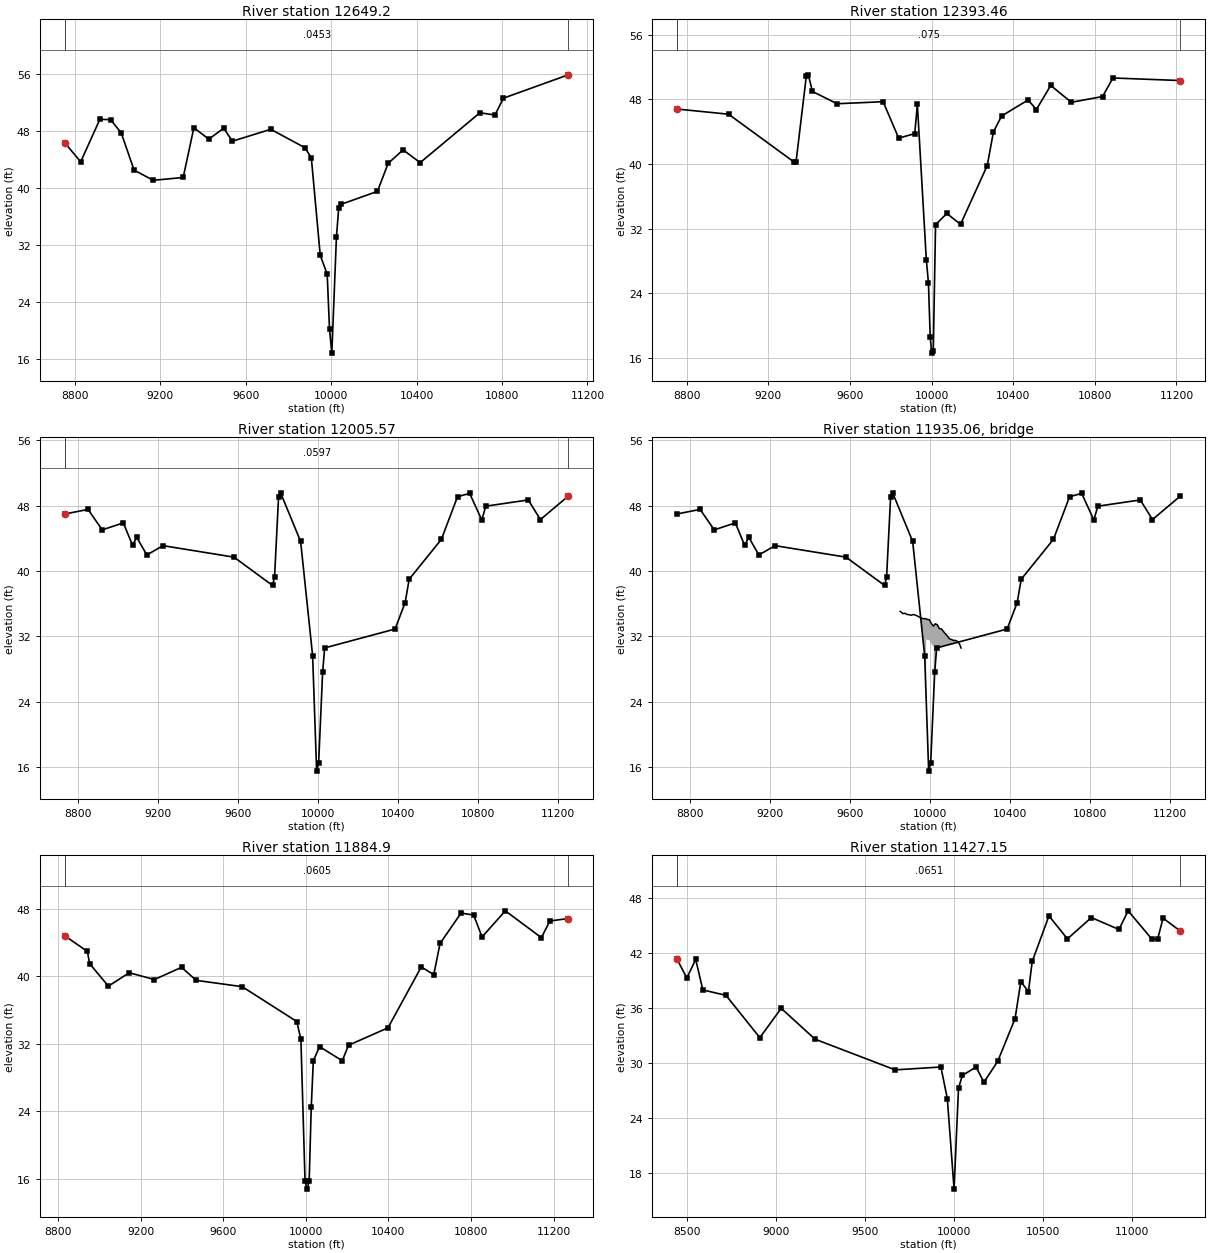
Type RM Length L Ch R = 1 , 12649.2,255.745800,255.745800,255.745800
XS GIS Cut Line= 6
791681.364175975865233.078484267792855.203071803865255.462129608
792921.219875723865227.294255316792923.112301826865226.647166952
792970.998775721865207.268872663794028.257320911865228.199288532
#Sta/Elev= 30
8753.17346.272358826.82243.643928916.838 49.60368966.84749.556639016.85647.69062
9076.86742.479949166.88441.047519306.90941.440849356.91848.423879426.93146.81841
9496.94448.365369536.95146.529739716.98448.203819877.01345.621719907.01844.20446
9948.74930.529649981.36527.875499992.23820.1335610003.04 16.792710024.6133.07244
 10035.437.1987810046.1937.6738610216.6939.49352 10266.743.4210410336.7245.32058
10416.7343.5231610696.7950.53158 10766.850.2036710806.8152.5715711110.1255.84833
#Mann= 3 , 0 , 0
8753.173  0.0453       08753.173  0.0453       011110.12  0.0453       0
#XS Ineff= 2 , 0
       0                               0
Bank Sta=8753.173,11110.12
Exp/Cntr=0.3,0.1

Type RM Length L Ch R = 1 ,12393.46,387.887400,387.887400,387.887400
XS GIS Cut Line= 6
791665.843674826865362.090417439792118.139972376865300.266039894
792434.466094528865309.631019437793009.390189167865525.678085021
793218.527980026865561.290561827794066.202435991865416.763152815
#Sta/Elev= 30
8751.79346.810459004.40946.170139325.53340.243359335.53340.305229385.56250.86808
9395.57451.051099415.59848.989679536.21247.467819762.163 47.71949838.47343.19667
9917.12743.763779929.987 47.37739973.93128.133349984.20925.294319992.98418.59402
10000.4116.5522410007.9916.7747210019.17 32.475810074.4933.8617810141.6632.51851
10272.5939.8100810302.8243.9729210342.9145.9468910473.0547.9415210513.1646.73742
10583.6849.7342610684.7947.6448910837.6748.3597710888.7350.6605911218.6250.34282
#Mann= 3 , 0 , 0
8751.793   0.075       08751.793   0.075       011218.62   0.075       0
#XS Ineff= 2 , 0
       0                               0
Bank Sta=8751.793,11218.62
Exp/Cntr=0.3,0.1

Type RM Length L Ch R = 1 ,12005.57,120.673800,120.673800,120.673800
XS GIS Cut Line= 5
791331.137546003865882.171840757792390.165323794865708.560729653
792675.363952011865697.128742903793262.561157137865628.265590757
 793822.45699048865545.800312966
#Sta/Elev= 30
8735.55346.993298850.93647.54945 8921.8745.044539027.14245.900449073.87243.14431
9094.13944.144179144.80741.975949225.87443.112579580.54641.706529773.08238.24403
9783.21639.227079803.48349.124619813.55649.579479913.63643.633299973.68429.63263
  9993.715.5178810003.7116.5232910023.7227.6260510033.7330.5967610385.7732.90861
10436.11 36.145910456.2539.0003210617.3443.8886510697.94 49.098710758.5949.51319
10819.2346.2600910839.45 47.946111051.7248.7079911112.3646.30602 11251.349.17304
#Mann= 3 , 0 , 0
8735.553  0.0597       08735.553  0.0597       0 11251.3  0.0597       0
#XS Ineff= 2 , 0
       0                               0
Bank Sta=8735.553,11251.3
Exp/Cntr=0.3,0.1

Type RM Length L Ch R = 3 ,11935.06,,,
BEGIN DESCRIPTION:
END DESCRIPTION:
Bridge Culvert--1,0,-1,-1, 0
Deck Dist Width WeirC Skew NumUp NumDn MinLoCord MaxHiCord MaxSubmerge Is_Ogee
41.336900,38.000000,2.6,0, 42, 42, , , 0.95, 0, 0,0,,
 9851.01 9854.73 9864.90 9865.61 9875.07 9885.24 9895.41 9905.58 9915.75 9920.50
 9925.92 9936.09 9946.26 9956.43 9966.60 9975.38 9976.77 9981.00 9981.00 9986.94
 9995.83 9997.1010007.1510017.1910019.0010019.0010027.2410037.2910047.3410057.38
10060.3810067.4310077.4810079.6510087.4910097.5010107.5010117.5010127.5110137.51
10147.5110155.73
   35.07   35.01   34.79   34.80   34.84   34.69   34.67   34.59   34.68   34.67
   34.61   34.52   34.38   34.28   34.16   34.19   34.19   34.15   34.15   34.08
   34.05   34.05   33.58   33.27   33.32   33.32   33.56   33.41   32.95   32.93
   32.84   32.61   32.33   32.27   32.04   31.72   31.63   31.52   31.52   31.39
   31.09   30.58
 -964.93 -964.99 -965.21 -965.20 -965.16 -965.31 -965.33 -965.41 -965.32 -965.33
 -965.39 -965.48 -965.62 -965.72 -965.84 -965.81 -965.81 -965.85   31.65   31.58
   31.55   31.55   31.08   30.77   30.82 -966.68 -966.44 -966.59 -967.05 -967.07
 -967.16 -967.39 -967.67 -967.73 -967.96 -968.28 -968.37 -968.48 -968.48 -968.61
 -968.91 -969.42
 9851.01 9854.73 9864.90 9865.61 9875.07 9885.24 9895.41 9905.58 9915.75 9920.50
 9925.92 9936.09 9946.26 9956.43 9966.60 9975.38 9976.77 9981.00 9981.00 9986.94
 9995.83 9997.1010007.1510017.1910019.0010019.0010027.2410037.2910047.3410057.38
10060.3810067.4310077.4810079.6510087.4910097.5010107.5010117.5010127.5110137.51
10147.5110155.73
   35.07   35.01   34.79   34.80   34.84   34.69   34.67   34.59   34.68   34.67
   34.61   34.52   34.38   34.28   34.16   34.19   34.19   34.15   34.15   34.08
   34.05   34.05   33.58   33.27   33.32   33.32   33.56   33.41   32.95   32.93
   32.84   32.61   32.33   32.27   32.04   31.72   31.63   31.52   31.52   31.39
   31.09   30.58
 -964.93 -964.99 -965.21 -965.20 -965.16 -965.31 -965.33 -965.41 -965.32 -965.33
 -965.39 -965.48 -965.62 -965.72 -965.84 -965.81 -965.81 -965.85   31.65   31.58
   31.55   31.55   31.08   30.77   30.82 -966.68 -966.44 -966.59 -967.05 -967.07
 -967.16 -967.39 -967.67 -967.73 -967.96 -968.28 -968.37 -968.48 -968.48 -968.61
 -968.91 -969.42
BR Coef=-1 , 0 , 0 ,, 0 ,,,0.8,0,1,0,
WSPro=,,,, 1 ,,,, 0 ,,,, 0 ,,,,-1 ,-1 ,-1 , 0 , 0 , 0 , 0 , 0
BC Design=,, 0 ,, 0 ,,,,,,

Type RM Length L Ch R = 1 , 11884.9,457.744100,457.744100,457.744100
XS GIS Cut Line= 6
791437.474351615866003.699618518792518.203518212865823.578090742
792776.172025621865810.857118845793177.406389803865764.268822163
793442.609151423865716.673667997 793841.10354203865622.748407736
#Sta/Elev= 30
8833.53244.787448942.43442.948918952.56241.521639043.714 38.83779144.99440.42688
9266.52939.623439398.19341.069069469.08939.525939691.90438.777179956.09134.65126
9976.121 32.54689996.15115.7082710006.1714.7968110016.1815.75614 10026.224.47928
10036.2129.9922510066.2631.6799610176.3630.0006210206.7131.8402110397.84 33.9045
10558.9341.1140210619.5840.2063410649.9843.8997910751.4947.49228 10812.647.26448
10853.3444.6628710965.87 47.761911140.5844.58379 11181.846.5581711270.5446.84988
#Mann= 3 , 0 , 0
8833.532  0.0605       08833.532  0.0605       011270.54  0.0605       0
#XS Ineff= 2 , 0
       0                               0
Bank Sta=8833.532,11270.54
Exp/Cntr=0.3,0.1

Type RM Length L Ch R = 1 ,11427.15,457.744100,457.744100,457.744100
XS GIS Cut Line= 6
791429.951188505866277.205362424792844.442864239866219.574134678
793006.270627201866007.363863513793170.426097006865893.105296478
793354.549513102865827.767843232794078.433894187865637.028170913
#Sta/Elev= 30
8444.51741.342228499.61239.285028549.65341.300868589.68637.979358719.794 37.3943
8909.95232.781559030.05135.979479220.20932.618199670.58229.27896 9927.4929.58976
9963.64626.1464310001.5716.2941210026.4727.2829410047.9628.6716810125.3529.58744
10169.0327.9237410247.0130.22093 10344.234.8517410376.6438.8826910419.4637.80446
10440.6241.07926 10534.846.0401910638.53 43.5408   1077345.8591910928.0144.56372
10979.67 46.593811114.01 43.495811145.0143.4761911176.0145.7995811272.5644.39234
#Mann= 3 , 0 , 0
8444.517  0.0651       08444.517  0.0651       011272.56  0.0651       0
#XS Ineff= 2 , 0
       09786.825        10376.83       0
Bank Sta=8444.517,11272.56
Exp/Cntr=0.3,0.1

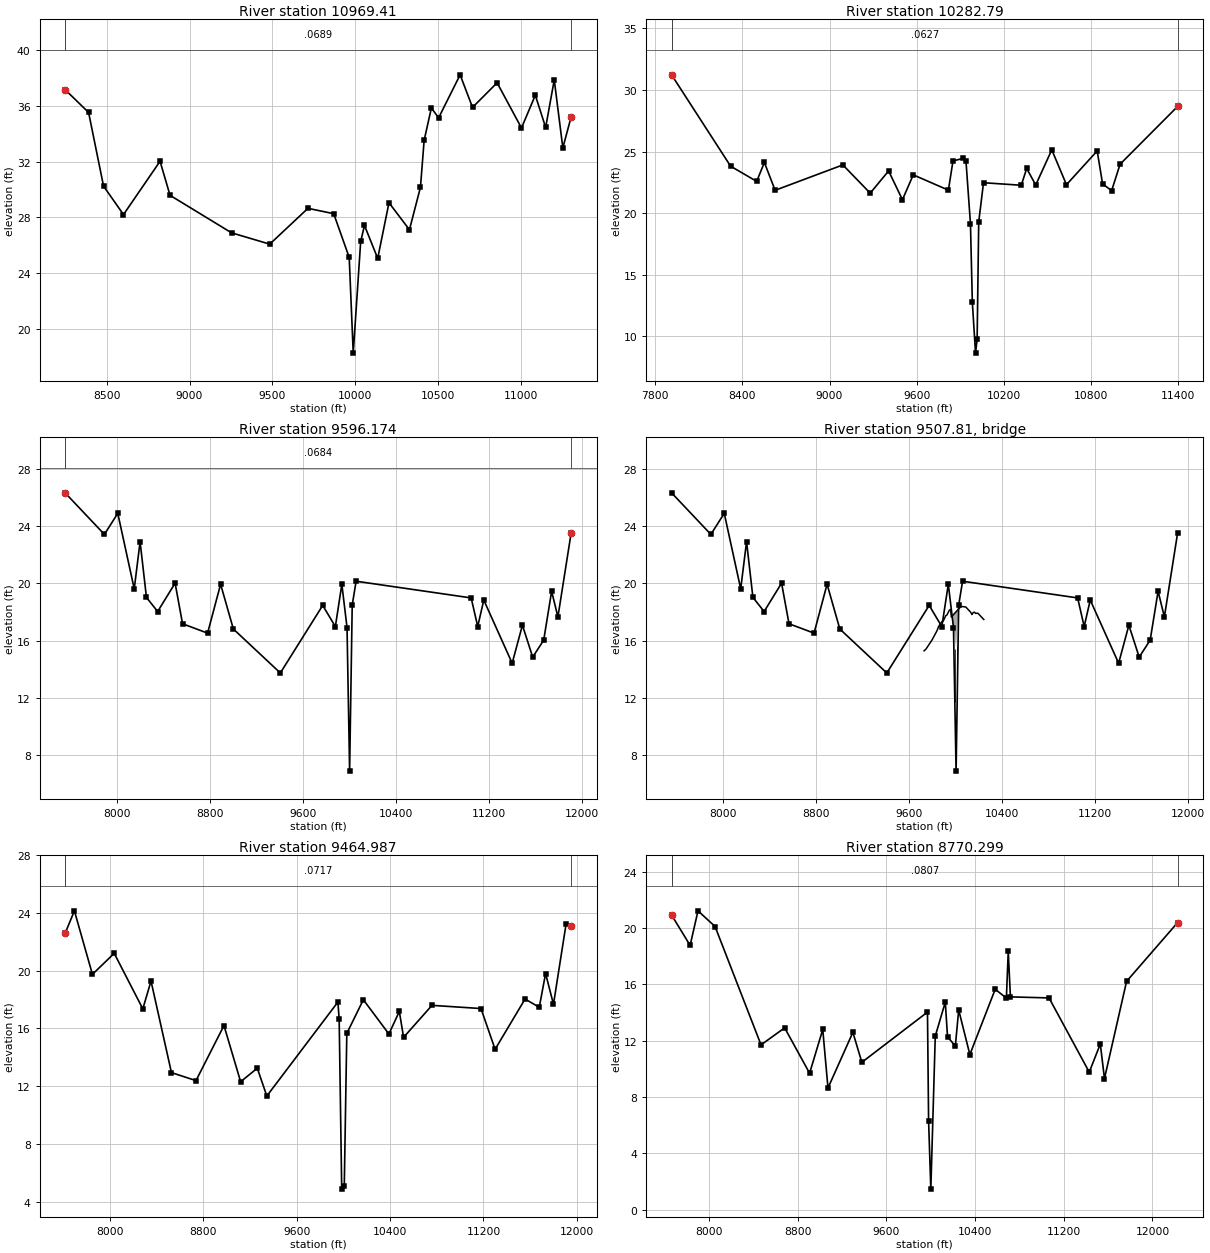
Type RM Length L Ch R = 1 ,10969.41,686.616200,686.616200,686.616200
XS GIS Cut Line= 6
791473.603531957866462.727821857792992.929531872866598.354583681
793381.752009124866371.685862437793683.871583164 866229.15452002
794047.956727594866096.781902015794393.662765861865995.959011674
#Sta/Elev= 30
8248.31837.144848390.27635.509958480.63430.241048601.112 28.20648821.98632.01965
8882.22529.583039253.69626.902779484.61126.090749715.525 28.65339871.01228.26942
9964.64825.14053 9988.9718.2950610033.9826.28013 10056.927.4284610136.83 25.0728
10204.9329.0534710328.5627.1200710395.0730.1603910417.2433.5065410461.0535.83408
10504.73 35.1246 10634.738.2024810709.6235.8721410858.1237.6336611005.3734.39926
11088.9536.7446411151.4134.4370511203.3237.8399511255.22 32.977111305.7435.20605
#Mann= 3 , 0 , 0
8248.318  0.0689       08248.318  0.0689       011305.74  0.0689       0
#XS Ineff= 2 , 0
       09710.475        10257.44       0
Bank Sta=8248.318,11305.74
Exp/Cntr=0.3,0.1

Type RM Length L Ch R = 1 ,10282.79,686.616100,686.616100,686.616100
XS GIS Cut Line= 6
791549.995132864866735.554968089793109.940042019 867265.61947833
793511.098113239867082.237899303793606.454537272867039.162544146
793731.110782564866987.478681043794660.224599928866299.031534106
#Sta/Elev= 30
7912.372 31.22548318.99623.807418498.54222.57399 8551.3524.111118625.28121.85132
 9091.7623.912019280.09721.618339406.83523.425019501.88921.084539576.47323.10487
9818.36621.861869850.06124.235949922.22524.448069939.31224.247659970.33419.13029
9983.29312.7580310005.288.63152910016.259.77401610027.2319.2917110060.1522.46588
 10320.122.2604210357.4423.6211310419.6722.2801410530.2925.1383710631.2522.30664
10842.8325.0464310880.17 22.3636 10942.421.82587 11000.623.9705911396.9628.66252
#Mann= 3 , 0 , 0
7912.372  0.0627       07912.372  0.0627       011396.96  0.0627       0
#XS Ineff= 2 , 0
       09604.534        10220.74       0
Bank Sta=7912.372,11396.96
Exp/Cntr=0.3,0.1

Type RM Length L Ch R = 1 ,9596.174,131.187400,131.187400,131.187400
XS GIS Cut Line= 6
791582.734390438 866959.27322799792679.499518245867799.580838397
793344.995064646867897.241791621793583.074883342867797.726946741
793870.156389713867655.693981558795139.255524486866491.122446135
#Sta/Elev= 30
 7554.2726.325267892.53523.424748007.63224.894228149.21519.624278199.60622.91694
8254.268 19.02948350.77818.042738500.904  20.0238564.93817.189598780.426 16.5356
8892.47819.948559002.14116.823729406.42613.755539771.14418.472189879.90916.99011
9935.69319.946159980.32116.9212810002.646.90784110024.9518.4881810058.4220.15721
11048.5218.9930711104.9316.99737 11157.118.84398 11401.414.4348211489.4817.09045
11578.2314.8621611672.8516.0525111740.9219.45514   1179517.6673111909.3523.54747
#Mann= 3 , 0 , 0
 7554.27  0.0684       0 7554.27  0.0684       011909.35  0.0684       0
#XS Ineff= 2 , 0
       09521.746        10245.32       0
Bank Sta=7554.27,11909.35
Exp/Cntr=0.3,0.1

Type RM Length L Ch R = 3 , 9507.81,,,
BEGIN DESCRIPTION:
END DESCRIPTION:
Bridge Culvert--1,0,-1,-1, 0
Deck Dist Width WeirC Skew NumUp NumDn MinLoCord MaxHiCord MaxSubmerge Is_Ogee
42.343700,46.500000,2.6,0, 25, 25, , , 0.95, 0, 0,0,,
 9727.07 9744.33 9797.11 9839.34 9851.43 9881.56 9892.11 9913.90 9923.78 9944.89
 9955.45 9961.80 9972.24 9972.2410032.2410032.2410047.0310086.1210128.6310139.26
10149.8910160.0010171.1510189.5110241.07
   15.30   15.43   16.08   16.72   16.99   17.35   17.38   17.75   17.80   18.14
   18.19   17.66   17.76   17.76   18.29   18.29   18.40   18.36   17.99   17.83
   17.97   18.00   17.91   17.93   17.49
 -984.70 -984.57 -983.92 -983.28 -983.01 -982.65 -982.62 -982.25 -982.20 -981.86
 -981.81 -982.34 -982.24   15.26   15.79 -981.71 -981.60 -981.64 -982.01 -982.17
 -982.03 -982.00 -982.09 -982.07 -982.51
 9727.07 9744.33 9797.11 9839.34 9851.43 9881.56 9892.11 9913.90 9923.78 9944.89
 9955.45 9961.80 9966.70 9966.7010026.7010026.7010047.0310086.1210128.6310139.26
10149.8910160.0010171.1510189.5110241.07
   15.30   15.43   16.08   16.72   16.99   17.35   17.38   17.75   17.80   18.14
   18.19   17.66   17.71   17.71   18.24   18.24   18.40   18.36   17.99   17.83
   17.97   18.00   17.91   17.93   17.49
 -984.70 -984.57 -983.92 -983.28 -983.01 -982.65 -982.62 -982.25 -982.20 -981.86
 -981.81 -982.34 -982.29   15.21   15.74 -981.76 -981.60 -981.64 -982.01 -982.17
 -982.03 -982.00 -982.09 -982.07 -982.51
Pier Skew, UpSta & Num, DnSta & Num=  ,9991.91, 2 ,9986.36, 2 , 0 , 0 , 0 ,,
    2.00    2.00
 -982.07   17.93
    2.00    2.00
 -982.12   17.88
Pier Skew, UpSta & Num, DnSta & Num=  ,10012.58, 2 ,10007.03, 2 , 0 , 0 , 0 ,,
    2.00    2.00
 -981.89   18.11
    2.00    2.00
 -981.93   18.07
BR Coef=-1 , 0 , 0 ,, 0 ,,,0.8,0,1,0,
WSPro=,,,, 1 ,,,, 0 ,,,, 0 ,,,,-1 ,-1 ,-1 , 0 , 0 , 0 , 0 , 0
BC Design=,, 0 ,, 0 ,,,,,,

Type RM Length L Ch R = 1 ,9464.987,694.688500,694.688500,694.688500
XS GIS Cut Line= 6
791604.560562104867313.948518082792739.521490455867996.016383678
793242.966221184868093.792760581793622.224081844867915.174542323
793964.528799087867772.550173327795227.341221184866625.697816074
#Sta/Elev= 30
7618.28322.584937697.97824.148997852.13219.747668038.80221.204048283.80617.35451
8353.80719.28439 8528.8112.939518738.813 12.38428978.566 16.19949121.182 12.3064
9263.798 13.24559345.29311.31617 9953.8617.828729964.76616.650599986.5784.865647
10008.395.063784 10030.215.6554110171.72 17.988510390.5815.6152510479.8217.17753
10516.28 15.381710759.4417.5993911178.9217.3780411299.7714.5547811556.4318.03747
11678.0117.4655711732.0419.8050411799.5917.6714611907.6523.2421811951.3423.09634
#Mann= 3 , 0 , 0
7618.283  0.0717       07618.283  0.0717       011951.34  0.0717       0
#XS Ineff= 2 , 0
       0 9489.24        10270.17       0
Bank Sta=7618.283,11951.34
Exp/Cntr=0.3,0.1

Type RM Length L Ch R = 1 ,8770.299,694.688400,694.688400,694.688400
XS GIS Cut Line= 6
791713.691420585867488.557891682793144.387098908868396.621291384
793538.901983649868530.815993488793900.634501308868565.941191733
794122.495559543868592.251374766795238.618149906867095.686801121
#Sta/Elev= 30
7662.425 20.91777829.79318.760677900.85821.214318054.83220.101058469.37811.70001
8682.57312.908578907.6139.6845389026.05512.794659073.4318.6391529297.95712.58879
9378.73810.46191 9970.7814.02465 9980.826.319665 10000.91.45996910041.0712.32038
10131.4714.7362110151.5912.2816310222.0811.6087510252.2914.1807310352.99 11.0093
10581.6615.6455610682.5415.0223610699.2718.3278910718.8815.1053911067.2615.03243
11429.949.76502311529.7411.7595811567.179.30841711766.76 16.210112227.4720.38332
#Mann= 3 , 0 , 0
7662.425  0.0807       07662.425  0.0807       012227.47  0.0807       0
#XS Ineff= 2 , 0
       09358.982        10631.21       0
Bank Sta=7662.425,12227.47
Exp/Cntr=0.3,0.1

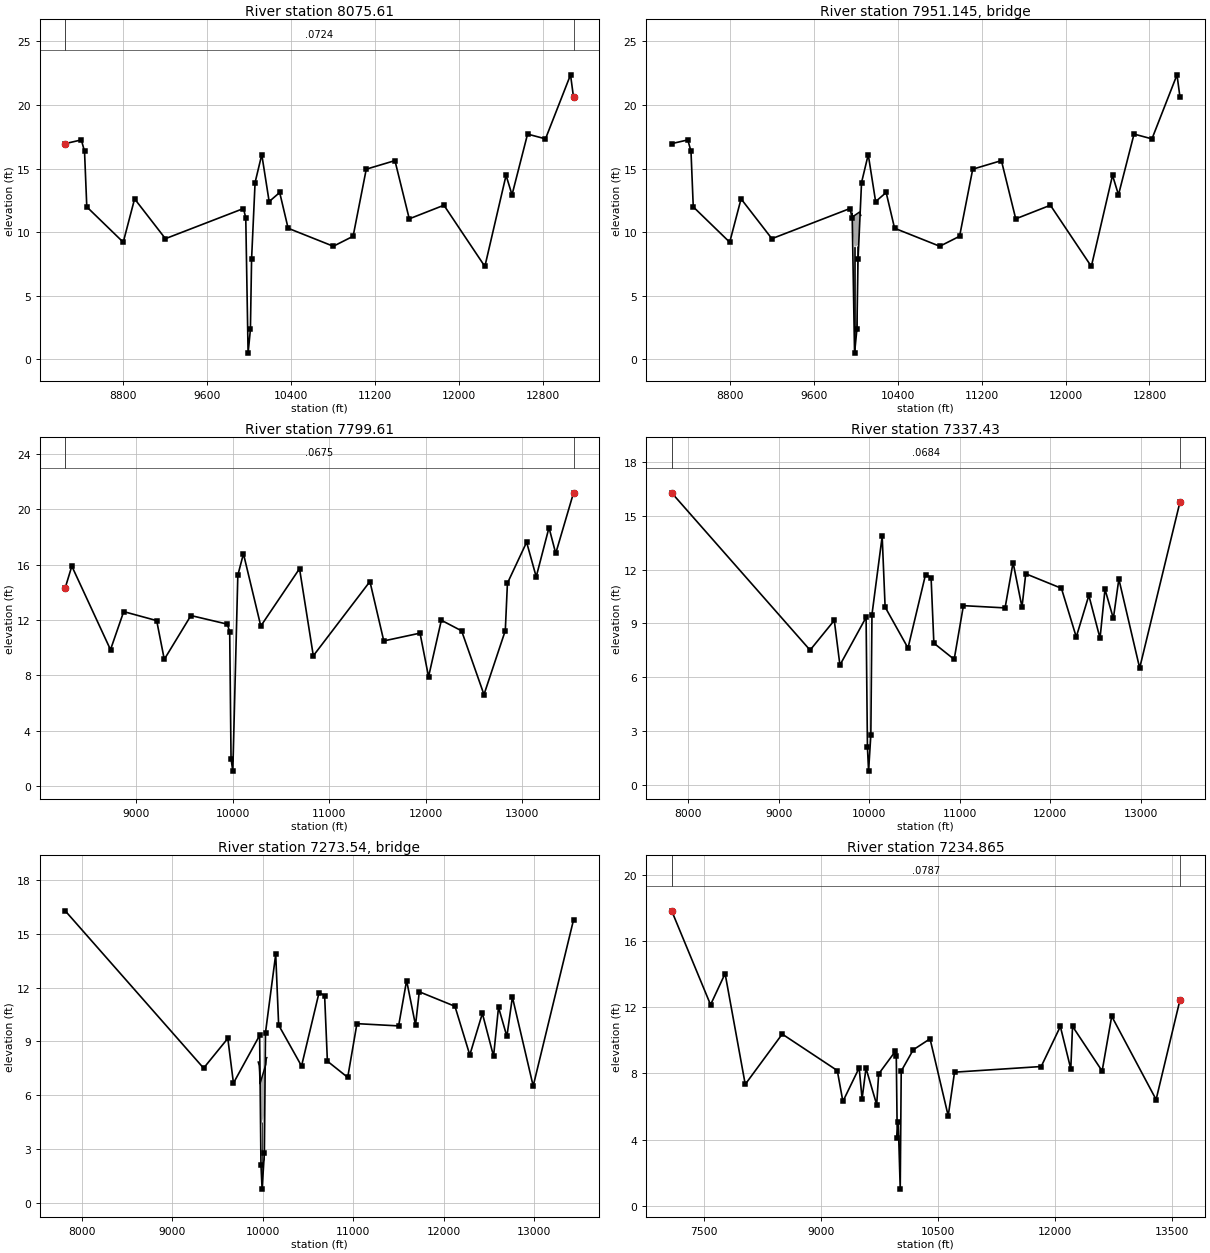
Type RM Length L Ch R = 1 , 8075.61,276.000000,276.000000,276.000000
XS GIS Cut Line= 6
 792124.55691424868196.552400768793385.553769499 869085.00000003
793488.274504781869175.443105102793639.655045718869248.293592811
794191.997969657869294.810072169795358.662094235867150.252230361
#Sta/Elev= 30
8247.79716.959678401.36217.251138431.83116.355418453.44911.987168800.6959.207305
8908.90812.617039202.4959.486089 9945.7811.854869967.98711.135149990.1950.487422
10012.382.35454710023.487.87987210056.76    13.910120.6416.0995710190.8912.40249
10291.2413.1168810371.5310.3066310802.278.89028410990.819.67646811116.0314.95059
11389.2515.6243611525.8511.0457911855.9912.1156912246.167.30277912447.96 14.4671
12504.8812.9345512652.8717.7104512823.6317.3336813062.2722.3689613090.8620.59561
#Mann= 3 , 0 , 0
8247.797  0.0724       08247.797  0.0724       013090.86  0.0724       0
#XS Ineff= 2 , 0
       09163.415        11208.77       0
Bank Sta=8247.797,13090.86
Exp/Cntr=0.3,0.1

Type RM Length L Ch R = 3 ,7951.145,,,
BEGIN DESCRIPTION:
END DESCRIPTION:
Bridge Culvert--1,0,-1,-1, 0
Deck Dist Width WeirC Skew NumUp NumDn MinLoCord MaxHiCord MaxSubmerge Is_Ogee
122.500000,31.000000,2.6,0, 10, 10, , , 0.95, 0, 0,0,,
 9960.70 9967.23 9968.41 9970.34 9970.3410030.3410030.3410037.5510039.2110049.33
   11.42   11.50   11.19   11.20   11.20   11.54   11.54   11.58   11.58   11.31
 -988.58 -988.50 -988.81 -988.80    8.70    9.04 -988.46 -988.42 -988.42 -988.69
 9960.70 9967.23 9968.41 9976.90 9976.9010036.9010036.9010037.5510039.2110049.33
   11.42   11.50   11.19   11.23   11.23   11.58   11.58   11.58   11.58   11.31
 -988.58 -988.50 -988.81 -988.77    8.73    9.08 -988.42 -988.42 -988.42 -988.69
Pier Skew, UpSta & Num, DnSta & Num=  ,9990.01, 2 ,9996.56, 2 , 0 , 0 , 0 ,,
    2.00    2.00
 -988.69   11.31
    2.00    2.00
 -988.65   11.35
Pier Skew, UpSta & Num, DnSta & Num=  ,10010.68, 2 ,10017.23, 2 , 0 , 0 , 0 ,,
    2.00    2.00
 -988.57   11.43
    2.00    2.00
 -988.53   11.47
BR Coef=-1 , 0 , 0 ,, 0 ,,,0.8,0,1,0,
WSPro=,,,, 1 ,,,, 0 ,,,, 0 ,,,,-1 ,-1 ,-1 , 0 , 0 , 0 , 0 , 0
BC Design=,, 0 ,, 0 ,,,,,,

Type RM Length L Ch R = 1 , 7799.61,462.180600,462.180600,462.180600
XS GIS Cut Line= 6
792093.977684438868300.521782085793223.452731222869263.580772936
793536.425893098 869562.41557464794083.167274863869606.461607173
794358.766953021869456.756537974795413.227523535867204.817659602
#Sta/Elev= 30
 8266.8414.313248335.392 15.88498736.1179.8471548872.69912.600249214.38211.94965
9293.2329.1493319569.20712.31574 9945.74 11.6942 9970.8811.145059984.8221.963878
10003.121.07578110055.1215.2301110113.37 16.779910293.01 11.556910694.3115.70262
 10837.19.408015 11423.614.7732411567.1410.4819511942.5711.0448312030.917.893231
12163.4111.9759812373.2111.2103212605.096.60498512825.9311.2273212848.0114.65375
13046.7717.6131313146.1515.1136513278.6518.6699413348.3516.8061813532.8221.18099
#Mann= 3 , 0 , 0
 8266.84  0.0675       0 8266.84  0.0675       013532.82  0.0675       0
#XS Ineff= 2 , 0
       09110.732        10672.53       0
Bank Sta=8266.84,13532.82
Exp/Cntr=0.3,0.1

Type RM Length L Ch R = 1 , 7337.43,102.564700,102.564700,102.564700
XS GIS Cut Line= 6
791844.648450822867996.016383678792846.080072939869581.277644768
793430.520445496869887.715752363794098.200678676  869753.0232054
794473.195800483869451.986415684795244.074692875867717.732694507
#Sta/Elev= 30
 7817.3516.272229346.4837.509942 9613.769.1662979676.1116.6762629965.2529.334527
9980.1272.1049049992.6530.77028410017.712.77731810030.239.49229710142.9713.84752
 10175.59.90718610428.317.62720510622.1411.7219610683.3511.5483210713.957.898441
10938.386.994702 11040.4 9.9879511500.789.86193711589.1512.3902911687.639.903821
11729.1611.7630512123.1210.9548312287.278.24278712426.2210.5580512549.918.170687
12604.6310.8995112697.039.27330612757.8411.4678412987.656.51316613433.3415.76754
#Mann= 3 , 0 , 0
 7817.35  0.0684       0 7817.35  0.0684       013433.34  0.0684       0
#XS Ineff= 2 , 0
       08937.461         10799.6       0
Bank Sta=7817.35,13433.34
Exp/Cntr=0.3,0.1

Type RM Length L Ch R = 3 , 7273.54,,,
BEGIN DESCRIPTION:
END DESCRIPTION:
Bridge Culvert--1,0,-1,-1, 0
Deck Dist Width WeirC Skew NumUp NumDn MinLoCord MaxHiCord MaxSubmerge Is_Ogee
36.282350,30.000000,2.6,0, 12, 12, , , 0.95, 0, 0,0,,
 9949.66 9954.84 9960.59 9964.86 9969.42 9972.23 9972.2310032.2310032.2310033.81
10039.2510045.05
    7.85    7.76    7.65    7.31    6.64    6.69    6.69    7.69    7.69    7.71
    8.07    8.09
 -992.15 -992.24 -992.35 -992.69 -993.36 -993.31    4.19    5.19 -992.31 -992.29
 -991.93 -991.91
 9949.66 9954.84 9960.59 9964.86 9969.42 9970.48 9970.4810030.4810030.4810033.81
10039.2510045.05
    7.85    7.76    7.65    7.31    6.64    6.66    6.66    7.66    7.66    7.71
    8.07    8.09
 -992.15 -992.24 -992.35 -992.69 -993.36 -993.34    4.16    5.16 -992.34 -992.29
 -991.93 -991.91
Pier Skew, UpSta & Num, DnSta & Num=  ,9991.90, 2 ,9990.14, 2 , 0 , 0 , 0 ,,
    2.00    2.00
 -992.99    7.01
    2.00    2.00
 -993.01    6.99
Pier Skew, UpSta & Num, DnSta & Num=  ,10012.57, 2 ,10010.81, 2 , 0 , 0 , 0 ,,
    2.00    2.00
 -992.64    7.36
    2.00    2.00
 -992.67    7.33
BR Coef=-1 , 0 , 0 ,, 0 ,,,0.8,0,1,0,
WSPro=,,,, 1 ,,,, 0 ,,,, 0 ,,,,-1 ,-1 ,-1 , 0 , 0 , 0 , 0 , 0
BC Design=,, 0 ,, 0 ,,,,,,

Type RM Length L Ch R = 1 ,7234.865,665.045700,665.045700,665.045700
XS GIS Cut Line= 6
791293.537615448867575.862578481792524.984552056869464.052295849
793269.802493244 870040.55091016794132.635772467869898.325743139
794548.703171015869465.000000015795369.575180113 867810.49392423
#Sta/Elev= 30
7088.32217.809547587.13612.137557773.464 14.02068031.6867.3323958506.05910.36798
9212.1088.1651289283.9096.2992089492.5778.3288669530.0646.4521329580.0478.308577
9717.4996.1050739742.4917.9605669955.8359.3233189968.5229.0415869981.2094.105938
9993.897 5.0601610019.271.00614610031.968.13215410186.229.42009910401.4810.08207
10634.595.42756110715.678.06736611826.928.40888612072.5110.8277212206.478.260602
 12228.810.8340112608.348.13579812731.14 11.445313300.466.41297613606.8912.43625
#Mann= 3 , 0 , 0
7088.322  0.0787       07088.322  0.0787       013606.89  0.0787       0
#XS Ineff= 2 , 0
       08973.256        10737.29       0
Bank Sta=7088.322,13606.89
Exp/Cntr=0.3,0.1

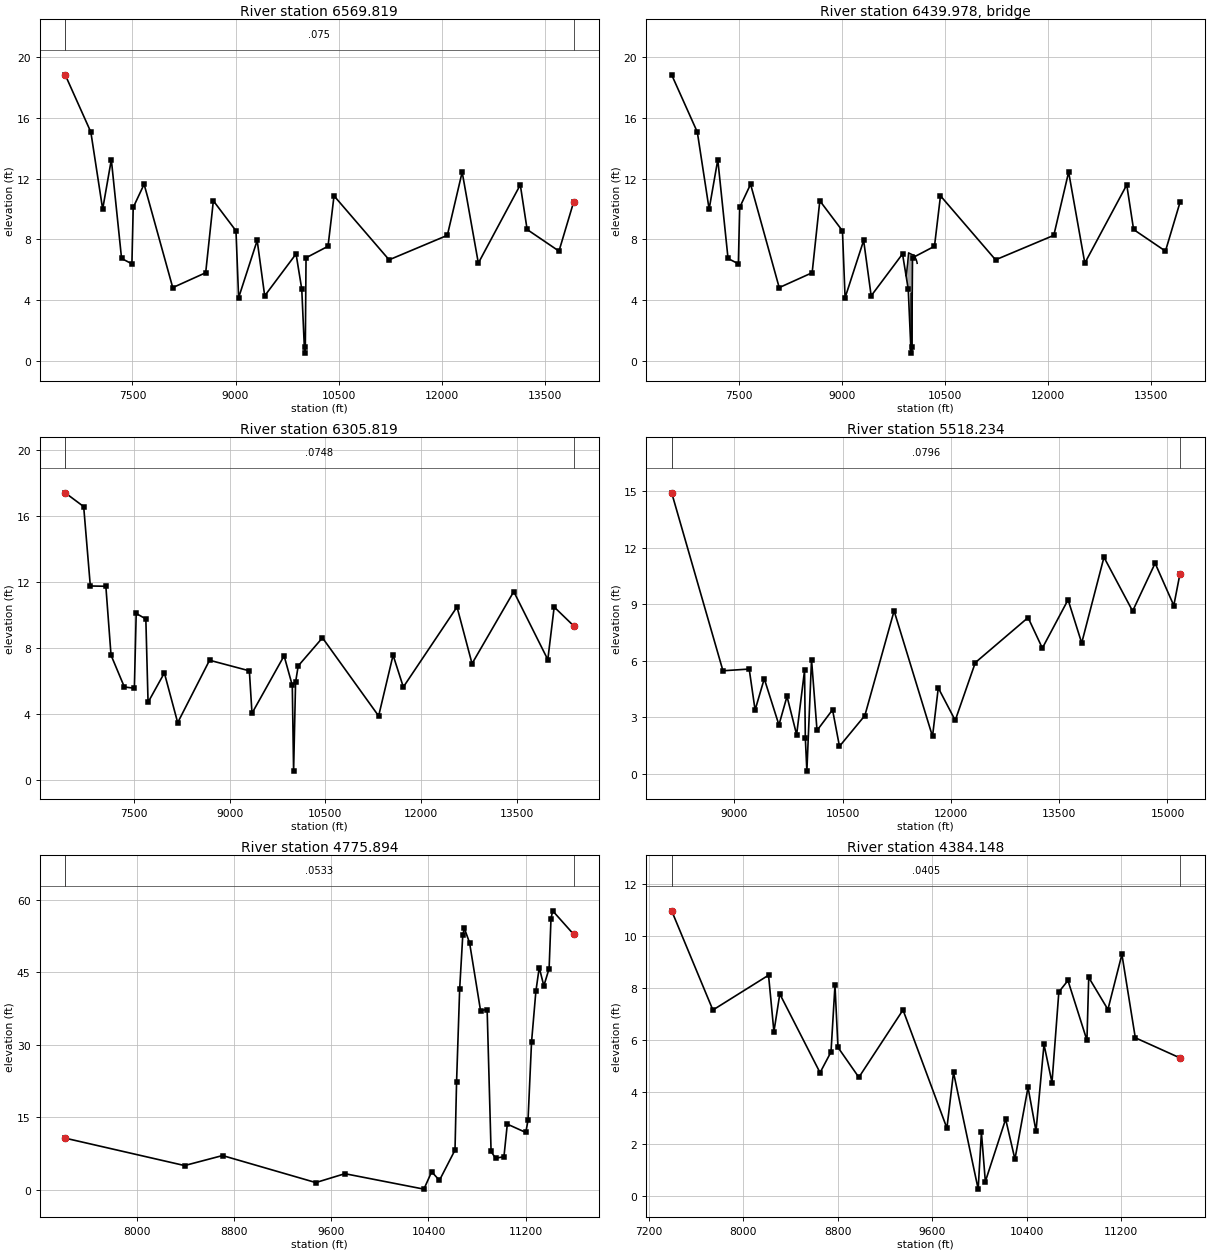
Type RM Length L Ch R = 1 ,6569.819,264.000000,264.000000,264.000000
XS GIS Cut Line= 6
790895.209981918867739.558866203792253.857474506870021.596505821
792718.970650822870454.765849888793055.130727261870545.000000015
794332.832024425869813.045177579795456.879866928867843.233181775
#Sta/Elev= 30
6520.94318.838946894.13915.06671 7066.159.9855137192.29113.249167341.3676.738977
7491.7466.3862887510.92410.101367669.39211.630178086.2574.8190848565.7025.799836
8677.25610.541289006.7918.5604469045.1464.1522479315.4127.9263649424.7334.277228
9881.2777.0386489964.2654.72298810005.750.50290410016.130.937003 10026.56.783648
10346.397.54303610433.7710.8670111235.566.64994312083.248.26317812299.1412.43262
12534.676.43325513145.2511.5906413244.638.64851413708.447.22344513920.2110.43684
#Mann= 3 , 0 , 0
6520.943   0.075       06520.943   0.075       013920.21   0.075       0
#XS Ineff= 2 , 0
       08767.254        10452.57       0
Bank Sta=6520.943,13920.21
Exp/Cntr=0.3,0.1

Type RM Length L Ch R = 3 ,6439.978,,,
BEGIN DESCRIPTION:
END DESCRIPTION:
Bridge Culvert--1,0,-1,-1, 0
Deck Dist Width WeirC Skew NumUp NumDn MinLoCord MaxHiCord MaxSubmerge Is_Ogee
116.500000,31.000000,2.6,0, 22, 22, , , 0.95, 0, 0,0,,
 9930.33 9933.95 9937.30 9945.88 9955.65 9957.80 9969.33 9969.72 9969.73 9977.75
 9977.7510027.7510027.7510041.9910046.0210051.0310060.6610061.1810071.3310081.47
10091.6210094.13
    5.63    5.59    5.72    6.04    6.41    6.53    7.09    7.11    7.11    7.09
    7.09    6.98    6.98    6.95    6.97    6.97    6.86    6.85    6.75    6.65
    6.49    6.42
 -994.37 -994.41 -994.28 -993.96 -993.59 -993.47 -992.91 -992.89 -992.89 -992.91
    4.59    4.48 -993.02 -993.05 -993.03 -993.03 -993.14 -993.15 -993.25 -993.35
 -993.51 -993.58
 9930.33 9933.95 9937.30 9945.88 9955.65 9957.80 9969.33 9969.72 9969.73 9981.48
 9981.4810031.4810031.4810041.9910046.0210051.0310060.6610061.1810071.3310081.47
10091.6210094.13
    5.63    5.59    5.72    6.04    6.41    6.53    7.09    7.11    7.11    7.08
    7.08    6.98    6.98    6.95    6.97    6.97    6.86    6.85    6.75    6.65
    6.49    6.42
 -994.37 -994.41 -994.28 -993.96 -993.59 -993.47 -992.91 -992.89 -992.89 -992.92
    4.58    4.48 -993.02 -993.05 -993.03 -993.03 -993.14 -993.15 -993.25 -993.35
 -993.51 -993.58
Pier Skew, UpSta & Num, DnSta & Num=  ,9994.09, 2 ,9997.81, 2 , 0 , 0 , 0 ,,
    2.00    2.00
 -992.94    7.06
    2.00    2.00
 -992.95    7.05
Pier Skew, UpSta & Num, DnSta & Num=  ,10011.42, 2 ,10015.14, 2 , 0 , 0 , 0 ,,
    2.00    2.00
 -992.98    7.02
    2.00    2.00
 -992.99    7.01
BR Coef=-1 , 0 , 0 ,, 0 ,,,0.8,0,1,0,
WSPro=,,,, 1 ,,,, 0 ,,,, 0 ,,,,-1 ,-1 ,-1 , 0 , 0 , 0 , 0 , 0
BC Design=,, 0 ,, 0 ,,,,,,

Type RM Length L Ch R = 1 ,6305.819,787.585400,787.585400,787.585400
XS GIS Cut Line= 6
790786.079123437867865.059353471792130.051012427 870144.86069493
792759.891257852870741.283158556793276.646669447870905.247124165
793879.938961744870522.395757765795587.836897075867832.320095927
#Sta/Elev= 30
6419.84717.405896709.47616.569566813.54911.750917057.11311.733247138.2287.554192
7347.1475.6193677504.1455.544969 7533.0210.083227684.0429.7504247718.8934.686797
7974.4696.4727678183.577 3.453698683.1117.2430019307.2546.600433 9348.57 4.02373
9851.8777.5117259980.254 5.7184310000.880.51180310031.785.90453110072.996.898325
10453.338.60515511334.153.85993311560.647.55408611721.345.61565612563.0710.47822
12798.757.03595613452.8911.4107313986.727.28002814086.5310.4745314390.079.338027
#Mann= 3 , 0 , 0
6419.847  0.0748       06419.847  0.0748       014390.07  0.0748       0
#XS Ineff= 2 , 0
       08710.552        10671.08       0
Bank Sta=6419.847,14390.07
Exp/Cntr=0.3,0.1

Type RM Length L Ch R = 1 ,5518.234,742.340300,742.340300,742.340300
XS GIS Cut Line= 6
790900.666524827870342.329841271791582.118950784 870965.15234533
792619.189137608871495.645409867  793549.3218458871151.805139378
794054.548335284870653.352787957795686.054669738867848.689724714
#Sta/Elev= 30
8130.044 14.91068840.5825.4768279204.1525.5679579286.0073.3943239413.0375.054751
9616.3342.6055089728.0944.1181369861.5022.0864079971.1775.4983459981.9241.918304
10003.390.15630910067.94 6.0664910144.142.31176210359.043.40966210454.991.470991
10806.813.10218211211.958.65246911744.291.99611211824.264.56775212059.152.846361
12337.145.908243 13068.48.29651713266.176.67667313622.749.24145313811.456.949021
14119.9311.4949114517.148.64233314828.8811.1770715087.718.93503315173.5810.62691
#Mann= 3 , 0 , 0
8130.044  0.0796       08130.044  0.0796       015173.58  0.0796       0
#XS Ineff= 2 , 0
       09210.878         11220.1       0
Bank Sta=8130.044,15173.58
Exp/Cntr=0.3,0.1

Type RM Length L Ch R = 1 ,4775.894,391.745100,391.745100,391.745100
XS GIS Cut Line= 6
790442.316919148870342.329841271791436.785639644871433.487125084
791707.069538713871657.223953217792255.062311739871995.638920486
792833.176012486872683.923194945793419.113512456873243.819028288
#Sta/Elev= 30
 7410.2310.672658392.6125.0057098705.113 7.073959472.5511.4864529712.0353.322455
10362.28 0.13058 10426.33.71684910490.321.94813410618.368.21077810631.1622.26898
10656.7741.5529710682.3852.6929310695.1854.0836610738.3251.0714910828.4237.06627
10882.7837.2799910915.277.91853610951.946.52444111021.096.82766411048.7613.57366
 11200.911.8531911219.2414.3551211248.1930.5311611283.8941.0231211311.5545.96165
11349.5142.1708411392.9345.7556611408.37 56.0879 11422.2 57.688811593.8752.85391
#Mann= 3 , 0 , 0
 7410.23  0.0533       0 7410.23  0.0533       011593.87  0.0533       0
#XS Ineff= 2 , 0
       09134.257        10724.83       0
Bank Sta=7410.23,11593.87
Exp/Cntr=0.3,0.1

Type RM Length L Ch R = 1 ,4384.148,288.000000,288.000000,288.000000
XS GIS Cut Line= 6
790278.620631427870342.329841271791015.904237568871142.118163198
791366.877746582871597.108434618 791557.10461846871826.919719219
792124.894971728872424.896722287 793151.01768893873540.648522288
#Sta/Elev= 30
7395.39310.982227744.1427.165831 8215.078.5050748260.524 6.331528310.2757.784002
8650.988 4.755258743.6445.5539218777.283 8.115058802.5425.7296978979.3554.575791
9352.9027.1700999724.2842.6225329780.2084.7643029988.9450.27466810016.29 2.46229
10049.570.56628410221.522.967141 10299.91.42515410410.754.19249210478.332.505933
10545.915.84101610613.494.373902 10671.57.86039810748.658.30190410909.336.000125
10924.368.42046511086.767.18544511205.179.30749511318.466.09854211696.735.322155
#Mann= 3 , 0 , 0
7395.393  0.0405       07395.393  0.0405       011696.73  0.0405       0
#XS Ineff= 2 , 0
       09394.284        10790.88       0
Bank Sta=7395.393,11696.73
Exp/Cntr=0.3,0.1

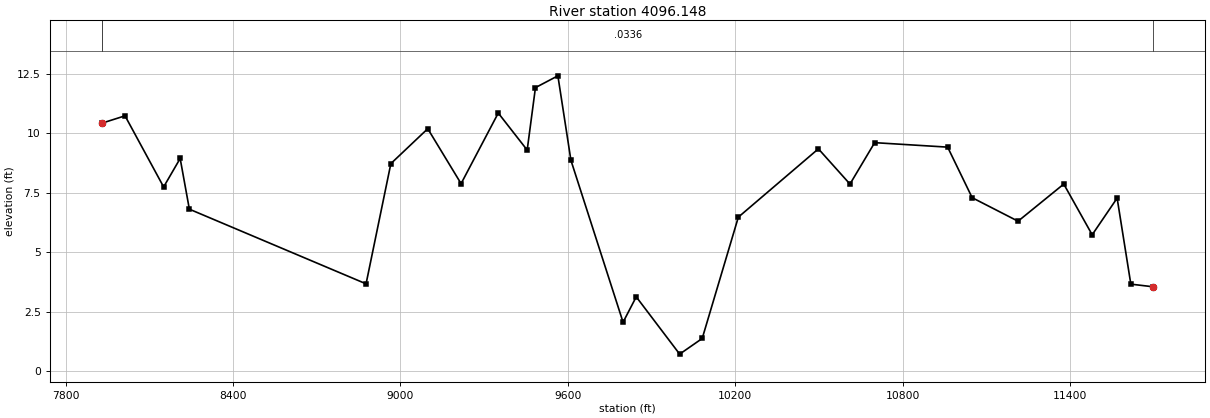
Type RM Length L Ch R = 1 ,4096.148,0.000000,0.000000,0.000000
XS GIS Cut Line= 6
790436.860376269870975.288820505791506.733461559872143.336975485
791649.780107021872357.183625087791914.020343035 872599.03922075
792052.856598109 872748.99993211792884.654676914873824.716690794
#Sta/Elev= 30
7932.10310.428048013.07610.729348151.427 7.742618210.648 8.938938243.6116.808843
8876.883  3.67398965.714 8.721919097.94310.187949217.4037.881358 9350.6510.84649
9454.2879.2913649483.89711.913679564.32712.409149611.043 8.862369797.9132.061157
9845.1173.12779310000.740.72167910081.581.37957610211.01 6.47394 10497.99.343016
10611.087.86315210699.58 9.6025110961.149.41440511049.017.29107911213.456.304002
 11377.37.86348511479.135.73391411568.557.27409311617.643.660693 11696.73.551166
#Mann= 3 , 0 , 0
7932.103  0.0336       07932.103  0.0336       0 11696.7  0.0336       0
#XS Ineff= 2 , 0
       09563.493        10757.26       0
Bank Sta=7932.103,11696.7
Exp/Cntr=0.3,0.1